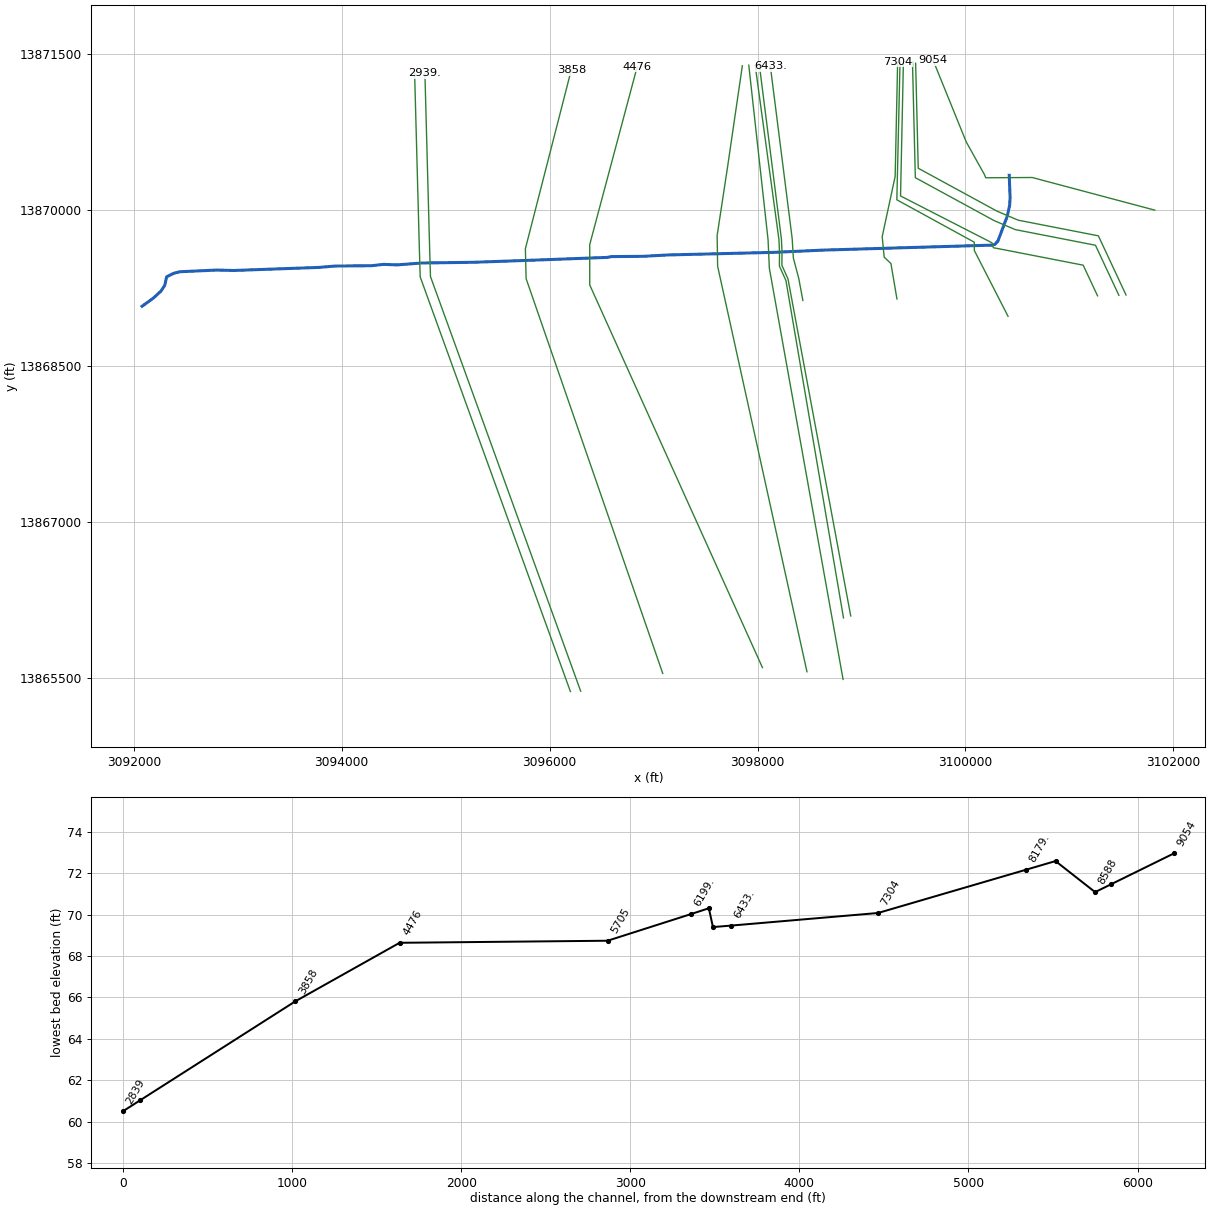
--- E116-05-00.prj (project) ---

Proj Title=E116-05-00
Current Plan=p01
Default Exp/Contr=.3,.1
English Units
Geom File=g01
Flow File=f04
Flow File=f01
Flow File=f02
Plan File=p04
Plan File=p01
Plan File=p02
Y Axis Title=Elevation
X Axis Title(PF)=Main Channel Distance
X Axis Title(XS)=Station
BEGIN DESCRIPTION:
White Oak Bayou Watershed
Schultz Gully
HCFCD Unit E116-05-00 and the downstream reach of E116-00-00
Flood Hazard Model
10, 2, 1, 0.2%
Filename E116-05-00
Prepared by:  Halff Associates, Inc.  DATE:  March 10, 2003
Reviewed by:  _________  DATE:  __________________
STATUS (Final)
END DESCRIPTION:
DSS File=dss
DSS Export Rating Curves= 0
DSS Export Rating Curve Sorted= 0
DSS Export Volume Flow Curves= 0
DXF OffsetX= 0
DXF OffsetY= 0
DXF ScaleX= 1
DXF ScaleY= 10

--- E116-05-00.p01 (plan) ---

Plan Title=FEMA Effective June 2007
Version=Version 3.0.1  Mar 2001
Short Identifier=FEMAeff0607
Geom File=g01
Flow File=f01
Subcritical Flow
K Sum by GR= 0
Std Step Tol= 0.01
Critical Tol= 0.01
Num of Std Step Trials= 20
Max Error Tol= 0.3
Flow Tol Ratio= 0.001
Split Flow NTrial= 30
Split Flow Tol= 0.02
Split Flow Ratio= 0.02
Log Output Level= 0
Friction Slope Method= 1
Unsteady Friction Slope Method= 2
Parabolic Critical Depth
Global Vel Dist= 0 , 0 , 0
Global Log Level= 0
CheckData=True
Encroach Param=-1 ,0,0, 0
Computation Interval=1HOUR
Output Interval=1HOUR
Run HTab= 0
Run UNet= 0
Run PostProcess= 0
UNET Theta= 1
UNET ZTol= 0.02
UNET ZSATol= 0.1
UNET MxIter= 20
UNET MaxInSteps= 20
UNET DtIC= 0
UNET DtMin= 0
UNET MaxCRTS= 20
UNET WFStab= 2
UNET SFStab= 1
UNET WFX= 1
UNET SFX= 1
UNET Convert EG Bridges=-1
UNET Use Existing IB Tables=-1
Instantaneous Interval=1HOUR
Write IC File= 0
IC Time=0
Write Velocity= 0
Write Detailed= 0

--- E116-05-00.p02 (plan) ---

Plan Title=Floodway
Version=Version 3.0.1  Mar 2001
Short Identifier=Floodway0607
Geom File=g01
Flow File=f02
Subcritical Flow
K Sum by GR= 0
Std Step Tol= 0.01
Critical Tol= 0.01
Num of Std Step Trials= 20
Max Error Tol= 0.3
Flow Tol Ratio= 0.001
Split Flow NTrial= 30
Split Flow Tol= 0.02
Split Flow Ratio= 0.02
Log Output Level= 0
Friction Slope Method= 1
Unsteady Friction Slope Method= 2
Parabolic Critical Depth
Global Vel Dist= 0 , 0 , 0
Global Log Level= 0
CheckData=True
Encroach Param=-1 ,0,0, 2
Encroach River=E116-05-00
Encroach Reach=Reach - 1
Encroach Node=9054
       1    4966  5039.1
Encroach Node=8683.
       1  4966.8  5046.8
Encroach Node=8588
       1 4978.64    5040
Encroach Node=8462
       1  4979.5  5087.5
Encroach Node=8354
       1 4980.37    5135
Encroach Node=8179.
       1  4965.1    5135
Encroach Node=7304
       1  4982.4    5080
Encroach Node=6433.
       1  4971.5  5036.7
Encroach Node=6328
       1  4971.5  5022.6
Encroach Node=6307
       1  4971.5  5022.6
Encroach Node=6304
       1  4971.5  5022.6
Encroach Node=6199.
       1  4967.5  5027.5
Encroach Node=5705
       1  4961.6    5022
Encroach Node=4476
       1  4931.7  5028.5
Encroach Node=3858
       1  4976.7  5026.3
Encroach Node=2939.
       1  4968.9  5038.9
Encroach Node=2839
       1  4971.3    5038
Encroach Node=2805
       1  4971.3    5038
Encroach Node=2778
       1  4971.3    5038
Encroach Node=2676.
       1  4956.9  5056.9
Encroach Node=2211
       1  4972.5    5037
Encroach Node=1349
       1  4956.3  5036.3
Encroach Node=1240
       1  4973.1  5032.2
Encroach Node=1206
       1  4973.1  5032.2
Encroach Node=1179
       1  4973.1  5032.2
Encroach Node=1077.
       1  4962.6  5032.6
Encroach Node=954
       1  4973.4  5024.4
Encroach Node=821
       1  4973.4  5024.4
Encroach Node=688
       1  4973.4  5024.4
Encroach Node=555
       1  4973.4  5024.4
Encroach Node=422
       1  4973.4  5024.4
Encroach Node=289
       1 4937.21 5053.99
Encroach Node=239
       14937.5455053.955
Encroach Node=163
       1 4937.88 5053.92
Encroach Node=130
       1  4927.3  5061.6
Encroach Reach=E116-05-00_0001
Encroach Node=9054
       1    4966  5039.1
Encroach Node=8683.
       1  4966.8  5046.8
Encroach Node=8588
       1 4978.64    5040
Encroach Node=8462
       1  4979.5  5087.5
Encroach Node=8354
       1 4980.37    5135
Encroach Node=8179.
       1  4965.1    5135
Encroach Node=7304
       1  4982.4    5080
Encroach Node=6433.
       1  4971.5  5036.7
Encroach Node=6328
       1  4971.5  5022.6
Encroach Node=6307
       1  4971.5  5022.6
Encroach Node=6304
       1  4971.5  5022.6
Encroach Node=6199.
       1  4967.5  5027.5
Encroach Node=5705
       1  4961.6    5022
Encroach Node=4476
       1  4931.7  5028.5
Encroach Node=3858
       1  4976.7  5026.3
Encroach Node=2939.
       1  4968.9  5038.9
Encroach Node=2839
       1  4971.3    5038
Encroach Node=2805
       1  4971.3    5038
Encroach Node=2778
       1  4971.3    5038
Encroach Node=2676.
       1  4956.9  5056.9
Encroach Node=2211
       1  4972.5    5037
Encroach Node=1349
       1  4956.3  5036.3
Encroach Node=1240
       1  4973.1  5032.2
Encroach Node=1206
       1  4973.1  5032.2
Encroach Node=1179
       1  4973.1  5032.2
Encroach Node=1077.
       1  4962.6  5032.6
Encroach Node=954
       1  4973.4  5024.4
Encroach Node=821
       1  4973.4  5024.4
Encroach Node=688
       1  4973.4  5024.4
Encroach Node=555
       1  4973.4  5024.4
Encroach Node=422
       1  4973.4  5024.4
Encroach Node=289
       1 4937.21 5053.99
Encroach Node=239
       14937.5455053.955
Encroach Node=163
       1 4937.88 5053.92
Encroach Node=130
       1  4927.3  5061.6
Computation Interval=1HOUR
Output Interval=1HOUR
Run HTab= 0
Run UNet= 0
Run PostProcess= 0
UNET Theta= 1
UNET ZTol= 0.02
UNET ZSATol= 0.1
UNET MxIter= 20
UNET MaxInSteps= 20
UNET DtIC= 0
UNET DtMin= 0
UNET MaxCRTS= 20
UNET WFStab= 2
UNET SFStab= 1
UNET WFX= 1
UNET SFX= 1
UNET Convert EG Bridges=-1
UNET Use Existing IB Tables=-1
Instantaneous Interval=1HOUR
Write IC File= 0
IC Time=0
Write Velocity= 0
Write Detailed= 0

--- E116-05-00.p04 (plan) ---

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Plan Title=Storage Routing
Program Version=3.13
Short Identifier=Store_Rout
Geom File=g01
Flow File=f04
Unsteady Bridges Friction Slope Method= 1
UNET Theta Warmup= 1
UNET DSS MLevel= 4
UNET DZMax Abort= 100
UNET Froude Reduction=False
UNET Froude Limit= 1
UNET Froude Power= 10
Echo Input=False
Echo Output=False
Detailed Automatic Start=False, 10

--- E116-05-00.f01 (steady flow) ---

Flow Title=FEMA Effective June 2007
Version=Version 3.0.1  Mar 2001
Number of Profiles= 4
Profile Names=10PCT_10yr, 2PCT_50yr, 1PCT_100yr, 0.2PCT_500yr
River Rch & RM=E116-05-00,E116-05-00_0001       ,9054
     260     370     440     600
River Rch & RM=E116-05-00,E116-05-00_0001       ,8588
     270     380     450     620
River Rch & RM=E116-05-00,E116-05-00_0001       ,8354
     290     420     490     680
River Rch & RM=E116-05-00,E116-05-00_0001       ,7304
     320     460     530     750
River Rch & RM=E116-05-00,E116-05-00_0001       ,6328
     350     510     590     840
River Rch & RM=E116-05-00,E116-05-00_0001       ,5705
     430     620     720    1040
River Rch & RM=E116-05-00,E116-05-00_0001       ,4476
     470     680     800    1160
River Rch & RM=E116-05-00,E116-05-00_0001       ,3858
     560     810     950    1400
River Rch & RM=E116-05-00,E116-05-00_0001       ,2778
    1500    2100    2400    3400
Boundary for River Rch & Prof#=E116-05-00,E116-05-00_0001       , 1
Up Type= 0
Dn Type= 3
Dn Slope=.00005
Boundary for River Rch & Prof#=E116-05-00,E116-05-00_0001       , 2
Up Type= 0
Dn Type= 3
Dn Slope=.00005
Boundary for River Rch & Prof#=E116-05-00,E116-05-00_0001       , 3
Up Type= 0
Dn Type= 3
Dn Slope=.00005
Boundary for River Rch & Prof#=E116-05-00,E116-05-00_0001       , 4
Up Type= 0
Dn Type= 3
Dn Slope=.00005
DSS Import GetInterval= 0
DSS Import GetPeak= 0
DSS Import FillOption= 0

--- E116-05-00.f02 (steady flow) ---

Flow Title=Floodway
Version=Version 3.0.1  Mar 2001
Number of Profiles= 2
Profile Names=1PCT_100yr, 1PCTFloodway_100yrFW
River Rch & RM=E116-05-00,E116-05-00_0001       ,9054
     440     440
River Rch & RM=E116-05-00,E116-05-00_0001       ,8588
     450     450
River Rch & RM=E116-05-00,E116-05-00_0001       ,8354
     490     490
River Rch & RM=E116-05-00,E116-05-00_0001       ,7304
     530     530
River Rch & RM=E116-05-00,E116-05-00_0001       ,6328
     590     590
River Rch & RM=E116-05-00,E116-05-00_0001       ,5705
     720     720
River Rch & RM=E116-05-00,E116-05-00_0001       ,4476
     800     800
River Rch & RM=E116-05-00,E116-05-00_0001       ,3858
     950     950
River Rch & RM=E116-05-00,E116-05-00_0001       ,2778
    2400    2400
Boundary for River Rch & Prof#=E116-05-00,E116-05-00_0001       , 1
Up Type= 0
Dn Type= 3
Dn Slope=.00005
Boundary for River Rch & Prof#=E116-05-00,E116-05-00_0001       , 2
Up Type= 0
Dn Type= 3
Dn Slope=.00005
DSS Import GetInterval= 0
DSS Import GetPeak= 0
DSS Import FillOption= 0

--- E116-05-00.f04 (steady flow) ---

Flow Title=Storage Routing
Version=Version 3.0.1  Mar 2001
Number of Profiles= 7
Profile Names=.25x10% flood,.50x10% flood,10% flood,2% flood,1% flood,0.2% flood,1.25x0.2% flood
River Rch & RM=E116-05-00,E116-05-00_0001       ,9054
     200     400     660     860     880    1000    1360
River Rch & RM=E116-05-00,E116-05-00_0001       ,7304
     200     400     700     860     910    1060    1440
River Rch & RM=E116-05-00,E116-05-00_0001       ,4476
     200     400     760     860    1000    1180    1600
River Rch & RM=E116-05-00,E116-05-00_0001       ,2211
     200     400     840     860    1100    1300    1760
Boundary for River Rch & Prof#=E116-05-00,E116-05-00_0001       , 1
Up Type= 0
Dn Type= 3
Dn Slope=.00005
Boundary for River Rch & Prof#=E116-05-00,E116-05-00_0001       , 2
Up Type= 0
Dn Type= 3
Dn Slope=.00005
Boundary for River Rch & Prof#=E116-05-00,E116-05-00_0001       , 3
Up Type= 0
Dn Type= 3
Dn Slope=.00005
Boundary for River Rch & Prof#=E116-05-00,E116-05-00_0001       , 4
Up Type= 0
Dn Type= 3
Dn Slope=.00005
Boundary for River Rch & Prof#=E116-05-00,E116-05-00_0001       , 5
Up Type= 0
Dn Type= 3
Dn Slope=.00005
Boundary for River Rch & Prof#=E116-05-00,E116-05-00_0001       , 6
Up Type= 0
Dn Type= 3
Dn Slope=.00005
Boundary for River Rch & Prof#=E116-05-00,E116-05-00_0001       , 7
Up Type= 0
Dn Type= 3
Dn Slope=.00005
DSS Import GetInterval= 0
DSS Import GetPeak= 0
DSS Import FillOption= 0

--- E116-05-00.g01 (geometry) ---

Geom Title=E116-05-00 June 2007
Version=Version 3.0.1  Mar 2001

River Reach=E116-05-00      ,E116-05-00_0001
Reach XY= 30
      3100420.73      13870333.1      3100429.12     13870115.89
      3100424.49     13870043.81      3100401.05     13869937.04
      3100311.64     13869700.06      3100282.13     13869667.94
      3100255.22     13869660.99      3098633.69     13869613.25
        3098158.     13869591.55      3097133.69     13869566.38
      3096898.45     13869553.36       3096595.5     13869550.75
      3096552.96     13869542.94      3095762.17     13869513.43
      3095267.37     13869496.06      3094770.76     13869489.05
      3094529.53     13869470.89      3094401.92      13869476.1
       3094285.6     13869463.08      3093933.17      13869459.6
      3093779.53     13869446.58      3092958.35     13869417.07
      3092801.23     13869421.41      3092442.72     13869404.92
       3092386.3     13869391.03      3092315.98     13869356.31
      3092297.76     13869273.84       3092261.3     13869218.29
      3092188.38     13869151.45       3092079.5       13869073.

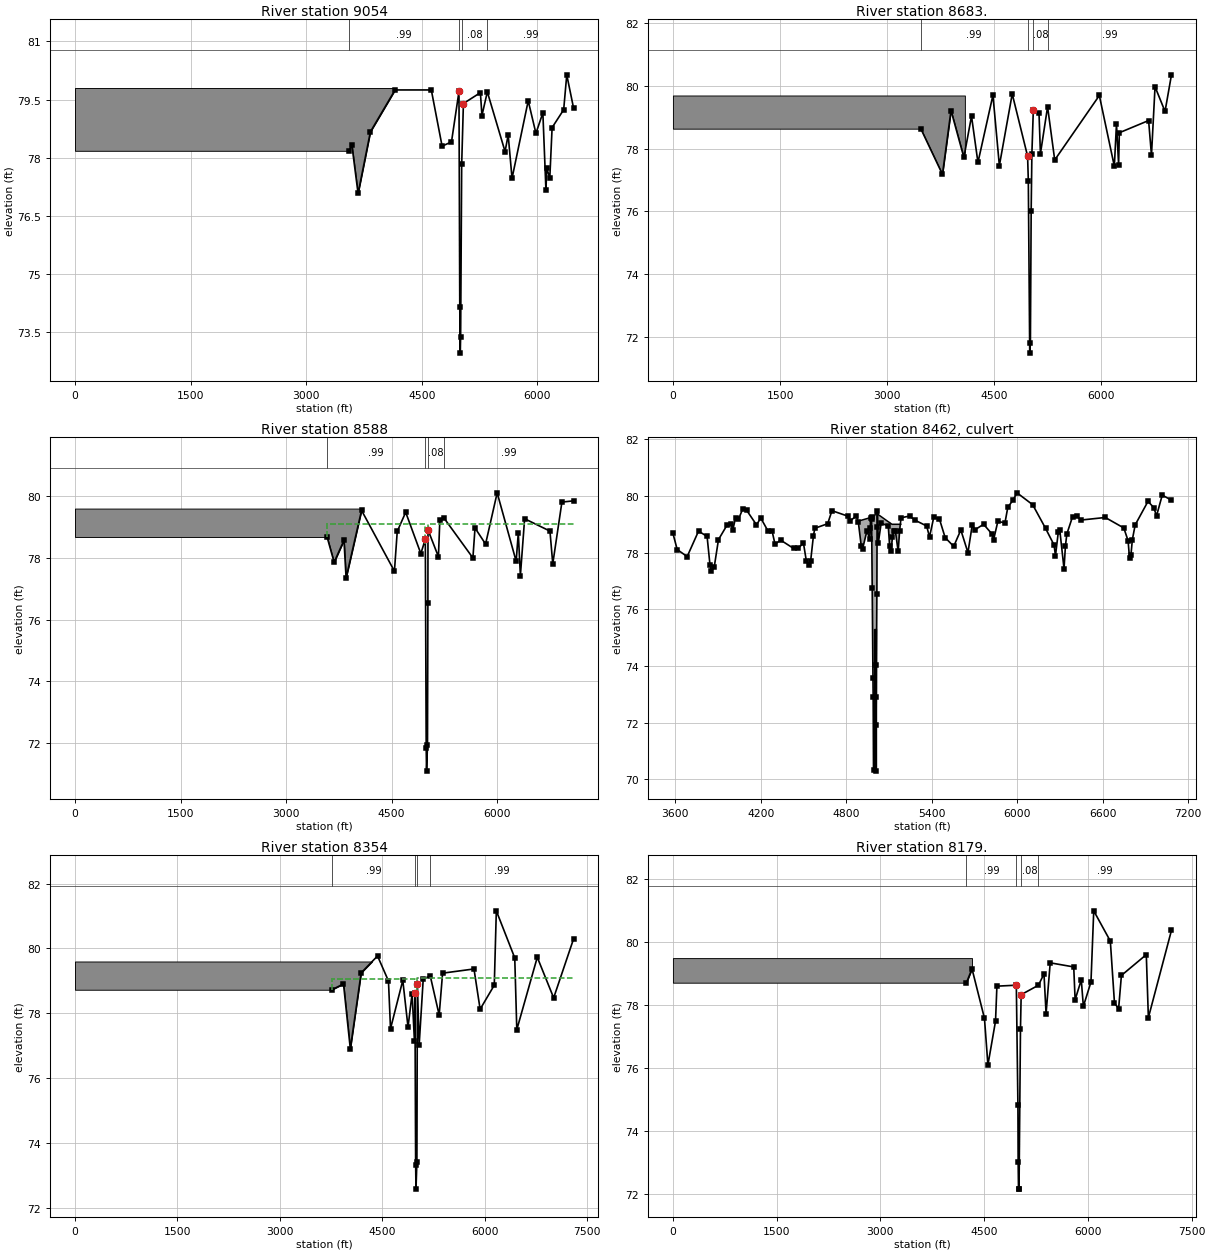
Type RM Length L Ch R = 1 ,9054    ,383,371,321
BEGIN DESCRIPTION:
Cross Section xs07
END DESCRIPTION:
XS GIS Cut Line= 6
      3101820.72      13869997.7       3100641.6     13870311.59
      3100194.83     13870308.94      3100182.09     13870339.89
      3100006.68     13870654.66      3099688.25      13871440.1
#Sta/Elev= 30
    3553   78.18  3592.7   78.32  3672.7   77.08  3832.7   78.67  4152.7   79.75
  4622.7   79.75  4762.7    78.3  4884.6   78.41  4981.6   79.71    4992   74.16
    4998   72.96  5003.1   73.38  5016.8   77.83  5039.1    79.4  5259.5   79.68
  5279.5   79.09  5349.5    79.7  5579.5   78.16  5619.9   78.59  5669.9   77.47
  5879.9   79.47  5979.9   78.63  6069.9   79.16  6109.9   77.16  6119.9   77.73
  6159.9   77.48  6189.9   78.78  6339.9   79.24  6379.9   80.14  6467.4   79.29
#Mann= 4 ,-1 , 0
    3553     .99       0  4981.6     .04       0  5016.8     .08       0
  5349.5     .99       0
#Block Obstruct= 2 , 0
       0    4150    79.8    6380       0    79.8
Bank Sta=4981.6,5039.1
XS Rating Curve= 0
Exp/Cntr=.3,.1

Type RM Length L Ch R = 1 ,8683.   ,96,95,94
BEGIN DESCRIPTION:
Interpolated channel - LIDAR overbanks
ELLA BOULEVARD - XS 4
END DESCRIPTION:
XS GIS Cut Line= 6
      3101544.08      13869181.6      3101278.05     13869750.57
       3100507.2     13869900.97      3100304.89     13869986.83
      3099545.46     13870400.63 3099520.525051313871410.2417221
#Sta/Elev= 30
    3471   78.64  3774.4   77.18  3894.4   79.22  4074.4   77.72  4181.4   79.04
  4271.4   77.56  4481.4   79.71  4571.4   77.46  4751.4   79.75  4966.8   77.76
  4976.8   76.98 4996.49   71.47 5005.96   71.78  5016.8   76.02  5026.8   77.84
  5046.8   79.23  5126.6   79.13  5146.6   77.84  5246.6   79.34  5346.6   77.64
  5971.4    79.7  6181.4   77.44  6211.4   78.79  6241.4   77.49  6251.4   78.51
  6661.4    78.9  6701.4   77.79  6751.4   79.98  6891.4   79.19  6981.4   80.36
#Mann= 4 ,-1 , 0
    3471     .99       0  4966.8     .04       0  5046.8     .08       0
  5246.6     .99       0
#Block Obstruct= 2 , 0
       04088.379    79.7               0
Bank Sta=4966.8,5046.8
XS Rating Curve= 0
Exp/Cntr=.5,.3

Type RM Length L Ch R = 1 ,8588    ,234,234,234
BEGIN DESCRIPTION:
Upstream Section of Bridge/Culvert/Weir
ELLA BOULEVARD - XS 3
END DESCRIPTION:
XS GIS Cut Line= 6
      3101475.33      13869178.3      3101250.15      13869659.9
       3100479.3      13869810.3      3100276.99     13869896.16
      3099517.56     13870309.96      3099490.04     13871424.24
#Sta/Elev= 30
  3582.6   78.68  3682.6   77.86  3822.6   78.57  3852.6   77.35  4072.6   79.54
  4539.6   77.57  4579.6   78.86  4699.6   79.48    4915   78.14 4978.64   78.61
    4991   71.84  4996.1   71.09  5009.4   71.93  5015.2   76.55  5016.5   78.91
  5164.8   78.04  5184.8   79.23  5244.8   79.29  5654.8      78  5684.8   78.97
  5834.8   78.45  5999.6   80.11  6269.6   77.89  6299.6   78.81  6329.6   77.43
  6389.6   79.27  6749.6   78.87  6789.6   77.81  6919.6   79.81  7084.3   79.85
#Mann= 4 ,-1 , 0
  3582.6     .99       0 4978.64     .04       0  5016.5     .08       0
  5244.8     .99       0
#XS Ineff= 2 , 0
       0 4978.91    79.1 5016.49       0    79.1
Permanent Ineff=
       F       F
#Block Obstruct= 2 , 0
       0  4072.6    79.6               0
Bank Sta=4978.64,5016.5
XS Rating Curve= 0
Exp/Cntr=.5,.3

Type RM Length L Ch R = 2 ,8462    ,,,
BEGIN DESCRIPTION:
ELLA BOULEVARD
Structure ID: E116-05-00-05
END DESCRIPTION:
Bridge Culvert--1,0,-1,-1, 0
Deck Dist Width WeirC Skew NumUp NumDn MinLoCord MaxHiCord MaxSubmerge Is_Ogee
10,210,2.6,0, 28, 28, , , .95, 0, ,,,
  4883.8  4965.2  4968.7  4971.4  4977.5    4978  4982.4  4987.7  4989.1    4991
  4996.1  4998.7  4999.8  5005.3  5008.7  5009.4  5010.8  5011.7  5015.2  5016.5
  5018.6  5025.2  5045.2  5095.2    5105    5115  5121.9    5183
   79.11   79.23    79.3    79.3    79.3    79.3    79.3    79.3    79.3    79.3
    79.3    79.3   79.31   79.37    79.4    79.4   79.39   79.39   79.38   79.37
   79.44   79.34   79.27   79.09   79.06   79.02      79      79
                                                                                
                                                                                
                                                                
  4883.8  4965.2  4968.7  4971.4  4977.5    4978  4982.4  4987.7  4989.1    4991
  4996.1  4998.7  4999.8  5005.3  5008.7  5009.4  5010.8  5011.7  5015.2  5016.5
  5018.6  5025.2  5045.2  5095.2    5105    5115  5121.9    5183
   79.11   79.23    79.3    79.3    79.3    79.3    79.3    79.3    79.3    79.3
    79.3    79.3   79.31   79.37    79.4    79.4   79.39   79.39   79.38   79.37
   79.44   79.34   79.27   79.09   79.06   79.02      79      79
                                                                                
                                                                                
                                                                
BR Coef= 1 , 0 , 0 ,1.25, 0 ,,,.8,0,2,0,
WSPro=,,,, 1 ,,,, 0 ,,,, 0 ,,,,-1 ,-1 ,-1 , 0 , 0 , 0 , 0 , 0
Culvert=2,5,8,210,.015,.4,1,8,1,70.32,4995.5,70.3,4995.5,Culvert #1  , 0 ,10
Culvert Bottom n=.015
Culvert=2,5,8,210,.015,.4,1,8,1,70.29,5004.2,70.31,5004.2,Culvert #2  , 0 ,10
Culvert Bottom n=.015
BR U #Sta/Elev= 110
  3582.6   78.68  3612.6   78.11  3682.6   77.86  3762.6   78.76  3822.6   78.57
  3842.6   77.58  3852.6   77.35  3872.6   77.49  3902.6   78.46  3962.6   78.97
  3992.6      79  4002.6   78.79  4022.6   79.23  4042.6   79.17  4072.6   79.54
  4099.6    79.5  4169.6   78.98  4199.6   79.22  4249.6   78.77  4279.6   78.75
  4299.6    78.3  4339.6   78.44  4429.6   78.15  4459.6   78.15  4499.6   78.33
  4519.6   77.71  4539.6   77.57  4549.6   77.69  4569.6    78.6  4579.6   78.86
  4669.6   79.02  4699.6   79.48  4809.6   79.29  4829.6   79.12  4869.6    79.3
    4885   79.07    4905   78.25    4915   78.14    4945   78.76    4965   78.49
  4968.7   78.88  4971.4   79.22  4977.5   79.25    4978   79.18  4982.4   76.74
  4987.7   73.59  4989.1    72.9  4991.5   70.32  5008.2   70.29  5009.4   71.93
  5010.8   72.89  5011.7   74.05  5015.2   76.55  5016.5   78.91  5018.6   79.47
  5025.2   78.34  5045.2   79.04  5095.2   78.94  5104.8   78.22  5114.8   78.05
  5124.8   78.56  5134.8   78.78  5144.8   78.77  5164.8   78.04  5174.8   78.77
  5184.8   79.23  5244.8   79.29  5284.8   79.14  5364.8   78.94  5384.8   78.55
  5414.8   79.25  5454.8   79.18  5494.8   78.53  5554.8   78.22  5604.8    78.8
  5654.8      78  5684.8   78.97  5704.8   78.81  5764.8      79  5824.8   78.65
  5834.8   78.45  5864.8    79.1  5914.8   79.05  5934.8    79.6  5969.6   79.84
  5999.6   80.11  6109.6   79.69  6199.6   78.86  6259.6   78.27  6269.6   77.89
  6289.6   78.73  6299.6   78.81  6329.6   77.43  6339.6   78.24  6349.6   78.66
  6389.6   79.27  6419.6   79.29  6449.6   79.15  6619.6   79.24  6749.6   78.87
  6779.6   78.42  6789.6   77.81  6799.6   77.91  6809.6   78.46  6829.6   78.98
  6919.6   79.81  6959.6   79.59  6979.6    79.3  7019.6   80.03  7084.3   79.85
BR U #Mann= 4
  3582.6     .99  4977.5     .04  5016.5     .08  5244.8     .99
BR U Banks=4977.5,
BR D #Sta/Elev= 111
    3765   78.73    3784   78.57    3814   78.95    3884   78.27    3934   78.91
    3964   78.62    4034   76.91    4064   76.95    4084   77.85  4092.8   78.08
  4192.8   79.25  4232.8   79.15  4432.8   79.77  4462.8   79.02  4482.8   79.05
  4492.8   79.33  4532.8   79.26  4562.8   78.92  4582.8    79.1  4592.8      79
  4602.8   78.69  4612.8   77.96  4622.8   77.53  4642.8   77.69  4662.8   78.54
  4682.8   78.92  4802.8   79.02  4842.8   78.58  4852.8   78.28  4862.8   77.74
  4879.3   77.58  4899.3   78.09  4939.3   78.61  4959.3   78.21  4968.7   78.88
  4971.4   79.22  4977.5   79.25 4979.32   79.27  4982.4   78.24  4987.7   75.09
  4989.1    74.4  4991.5    70.3  5008.2   70.31  5009.4   73.43  5010.8   74.39
  5011.7   75.55  5015.2   78.05  5016.5   78.91  5018.6   79.47  5025.2   78.34
  5045.2   79.04  5095.2   78.94  5102.3   79.07  5115.7   79.17  5165.7   79.32
  5205.7   79.15  5235.7   78.79  5265.7    79.1  5285.7   78.46  5315.7   78.36
  5335.7   77.95  5345.7   78.14  5355.7   78.63  5385.7   79.24  5435.7   79.12
  5455.7   78.46  5475.7   78.73  5485.7   79.06  5555.7   78.96  5605.7   79.34
  5675.7   78.84  5725.7   79.24  5755.7   78.74  5785.7   78.89  5845.7   79.37
  5865.7   79.17  5885.7   79.27  5915.7   78.91  5935.7   78.13  5965.7   78.78
    6013   78.77    6103   78.94    6123   78.72    6143   78.87    6153   80.04
    6163   80.82    6173   81.16    6283   80.41    6313   80.57    6443   79.71
    6453   79.45    6463   78.78    6473    77.5    6493   78.39    6503   78.66
    6513   78.71    6523   78.47    6533   77.82    6543   77.92    6553   78.24
    6563   78.81    6773   79.73    6803   79.48    6903   79.69    6913   79.59
    6923   79.28    6963   78.76    7003   78.69    7013   78.48    7033   78.77
  7303.7   80.29
BR D #Mann= 4
    3765     .99  4977.5     .04  5016.5     .08  5205.7     .99
BR D Banks=4977.5,
BC Design=,, 0 ,, 0 ,,,,,,
BC HTab HWMax=80.11

Type RM Length L Ch R = 1 ,8354    ,220,175,60
BEGIN DESCRIPTION:
Downstream Section of Bridge/Culvert/Weir
ELLA BOULEVARD - XS 2
END DESCRIPTION:
XS GIS Cut Line= 6
      3101270.39      13869173.2      3101131.87      13869468.2
       3100267.9     13869636.41      3100254.21     13869683.79
      3099375.26     13870133.87      3099402.83     13871424.24
#Sta/Elev= 30
    3765   78.73    3934   78.91    4034   76.91  4192.8   79.25  4432.8   79.77
  4592.8      79  4622.8   77.53  4802.8   79.02  4879.3   77.58  4939.3   78.61
    4973   77.16 4980.37   78.63    4991   73.34  4996.1   72.59  5009.4   73.43
  5016.5   78.91  5042.3   77.02  5102.3   79.07  5205.7   79.15  5335.7   77.95
  5385.7   79.24  5845.7   79.37  5935.7   78.13    6143   78.87    6173   81.16
    6443   79.71    6473    77.5    6773   79.73    7013   78.48  7303.7   80.29
#Mann= 4 ,-1 , 0
    3765     .99       0 4980.37     .04       0  5016.5     .08       0
  5205.7     .99       0
#XS Ineff= 2 , 0
       0 4980.15   79.07 5016.26       0   79.08
Permanent Ineff=
       F       F
#Block Obstruct= 2 , 0
       0    4350    79.6               0
Bank Sta=4980.37,5016.5
XS Rating Curve= 0
Exp/Cntr=.5,.3

Type RM Length L Ch R = 1 ,8179.   ,896,875,577
BEGIN DESCRIPTION:
Interpolated channel - LIDAR overbanks
ELLA BOULEVARD - XS 1
END DESCRIPTION:
XS GIS Cut Line= 6
  3100409.302551 13868976.425712      3100315.95      13869158.6
      3100084.98     13869609.33      3100084.43     13869689.29
      3099339.59     13870097.17      3099370.37     13871420.65
#Sta/Elev= 30
  4244.3   78.72  4324.3   79.16  4504.3   77.59  4554.3   76.11  4664.3    77.5
  4684.3   78.61  4965.1   78.64  4988.1   74.84 4991.43   73.03 4996.57   72.17
 5004.23   72.17  5025.1   77.26  5035.1   78.34  5285.1   78.64  5365.1      79
  5395.1   77.74  5455.1   79.35  5795.1   79.22  5815.1   78.18  5904.3   78.81
  5934.3   77.97  6044.3   78.74  6084.3      81  6324.3   80.04  6384.3   78.07
  6444.3    77.9  6484.3   78.95  6844.3   79.61  6874.3   77.61  7208.1   80.38
#Mann= 4 ,-1 , 0
  4244.3     .99       0  4965.1     .04       0  5035.1     .08       0
  5285.1     .99       0
#Block Obstruct= 2 , 0
       0  4324.3    79.5               0
Bank Sta=4965.1,5035.1
XS Rating Curve= 0
Exp/Cntr=.3,.1

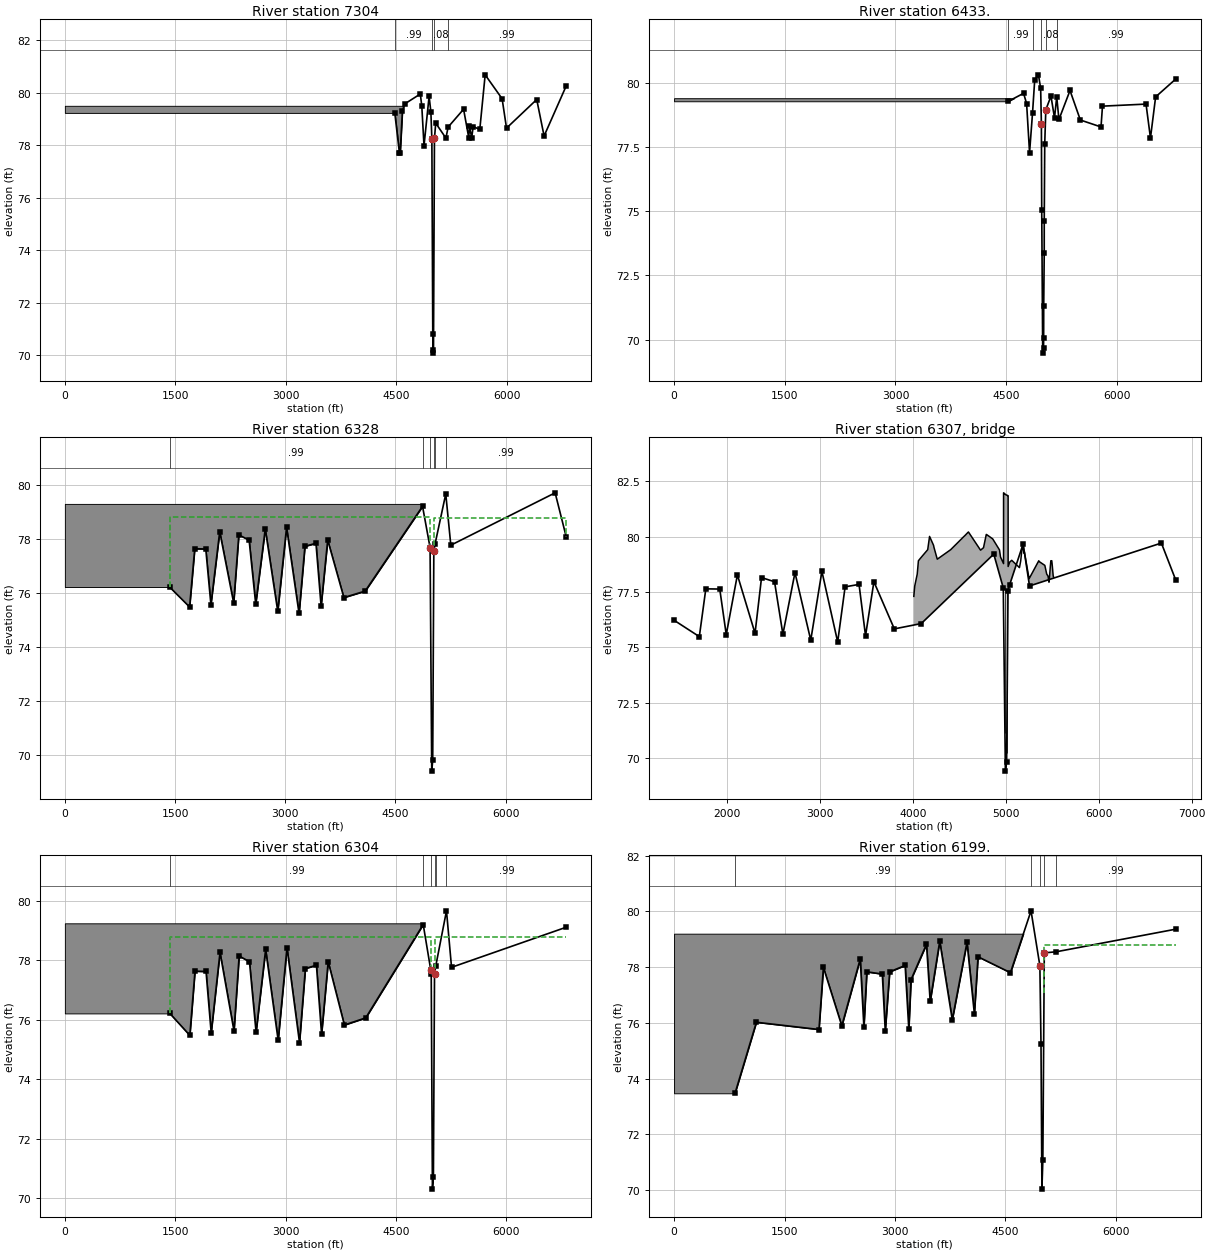
Type RM Length L Ch R = 1 ,7304    ,872,871,870
BEGIN DESCRIPTION:
Cross Section X06
END DESCRIPTION:
XS GIS Cut Line= 6
      3099340.75      13869143.1       3099282.8     13869483.86
      3099218.12      13869545.3      3099198.72     13869742.56
      3099323.54      13870322.2      3099347.33     13871424.24
#Sta/Elev= 30
    4479   79.23  4542.5   77.69  4552.5   77.72  4582.5    79.3  4612.5   79.57
  4825.7   79.95  4845.7   79.49  4875.7   77.98  4944.9   79.86    4969   79.27
  4982.4   78.24  4994.7   70.81  4998.9   70.08  5004.5   70.19  5017.6   78.26
  5034.9   78.84  5173.1   78.27  5203.1   78.69  5413.1   79.37  5483.1   78.29
  5493.1   78.72  5523.1   78.28  5543.1   78.71  5633.1    78.6    5706   80.68
    5936   79.77    5996   78.65    6406   79.74    6506   78.35  6808.3   80.27
#Mann= 4 ,-1 , 0
    4479     .99       0  4982.4     .04       0  5017.6     .08       0
  5203.1     .99       0
#Block Obstruct= 2 , 0
       0    4600    79.5               0
Bank Sta=4982.4,5017.6
XS Rating Curve= 0
Exp/Cntr=.3,.1

Type RM Length L Ch R = 1 ,6433.   ,104,105,106
BEGIN DESCRIPTION:
Interpolated channel - LIDAR overbanks
OAK FOREST DRIVE - XS 4
END DESCRIPTION:
XS GIS Cut Line= 6
      3098435.83      13869128.5      3098395.93     13869342.89
      3098395.32     13869343.71      3098344.19     13869537.32
       3098332.9     13869724.84 3098122.956081813871381.5611213
#Sta/Elev= 30
  4530.1   79.28  4735.4   79.59  4776.4   79.19  4816.4   77.28  4856.4   78.81
  4886.4   80.12  4936.7   80.31  4966.7   79.79  4976.7   78.39 4981.22   75.05
 4994.62   69.47 5005.78   69.67 5007.42   70.06 5008.19   71.31 5015.22   73.37
 5015.32   74.63 5022.06   77.63  5036.7   78.95  5106.7   79.48  5154.5   78.63
  5184.5   79.45  5214.5   78.57  5364.5    79.7  5504.5   78.55  5784.5   78.28
  5804.5   79.09  6394.5   79.17  6454.5   77.85  6524.5   79.45  6794.5   80.14
#Mann= 5 ,-1 , 0
  4530.1     .99       0  4856.4     .08       0  4976.7    .045       0
  5036.7     .08       0  5184.5     .99       0
#Block Obstruct= 2 , 0
       0  4735.4    79.4               0
Bank Sta=4976.7,5036.7
XS Rating Curve= 0
Exp/Cntr=.5,.3

Type RM Length L Ch R = 1 ,6328    ,24,24,24
BEGIN DESCRIPTION:
Upstream Section of Bridge/Culvert/Weir
OAK FOREST DRIVE - XS 3
END DESCRIPTION:
XS GIS Cut Line= 6
      3098896.09      13866094.3      3098292.47     13869337.08
      3098234.13     13869466.42      3098235.15     13869593.98
      3098229.44     13869719.03      3098015.36     13871408.39
#Sta/Elev= 30
    1426   76.22    1698   75.48    1768   77.64    1918   77.63    1988   75.57
    2108   78.27    2298   75.63    2368   78.15    2508   77.96    2598   75.59
    2728   78.37    2898   75.32    3018   78.43    3188   75.24    3268   77.73
    3418   77.84    3488   75.52    3578   77.96    3798   75.83    4088   76.07
    4869   79.21  4971.5   77.68  4994.1    69.4  5007.4    69.8  5022.6   77.55
  5040.6   77.83  5185.1   79.67  5253.9   77.77  6673.9   79.71  6826.7   78.06
#Mann= 6 ,-1 , 0
    1426     .99       0    4869     .08       0  4971.5    .045       0
  5022.6     .04       0  5040.6     .08       0  5185.1     .99       0
#XS Ineff= 2 , 0
       0    4971   78.81 5022.36       0   78.79
Permanent Ineff=
       F       F
#Block Obstruct= 2 , 0
       0    4868    79.3               0
Bank Sta=4971.5,5022.6
XS Rating Curve= 0
Exp/Cntr=.5,.3

Type RM Length L Ch R = 3 ,6307    ,,,
BEGIN DESCRIPTION:
OAK FOREST DRIVE
Structure ID: E116-05-00-04
END DESCRIPTION:
Bridge Culvert--1,0,-1,-1, 0
Deck Dist Width WeirC Skew NumUp NumDn MinLoCord MaxHiCord MaxSubmerge Is_Ogee
10,5,2.6,0, 82, 82, , , .95, 0, ,,,
    4008  4017.5  4044.8  4057.5  4074.8  4104.8  4157.5  4177.5  4220.4  4224.8
  4260.4  4404.8  4514.8  4524.8  4528.4  4558.4  4588.4  4596.3  4726.3    4730
  4758.4  4788.4    4800    4857    4869  4915.9  4930.7  4941.5 4974.29  4974.4
 4974.51  4974.6 4974.71  4974.8  4977.8  4980.3  4983.1  4987.8  4989.4  4991.3
  4994.1  4994.2  4996.6  4999.5  5005.6  5005.7  5007.4  5008.2  5009.8  5015.5
  5015.6  5022.6  5023.4 5023.49  5023.6 5023.71  5040.6  5062.5  5097.5  5138.7
  5145.7    5159  5168.8  5185.1  5193.7    5199  5203.7    5249  5253.7  5353.7
    5359    5419    5439  5453.7  5463.7    5469    5479  5483.7  5493.7    5499
    5509  5513.7
    77.3   77.76   78.31   78.91      79   79.15   79.41   80.01   79.61   79.52
   78.98   79.41   79.87   79.91   79.93   80.05   80.18   80.21   79.39    79.4
    79.5    80.1   80.07    79.9   79.82    79.5    79.4   79.08   78.78   81.98
   81.98   81.98   81.98   81.98   81.97   81.96   81.95   81.93   81.93   81.92
   81.91   81.91    81.9   81.89   81.88   81.88   81.88   81.88   81.88   81.86
   81.86   81.85   81.85   81.85   81.85   78.65   78.85   78.93   78.79   78.63
    78.6    78.9   79.29   79.67   79.25    79.3   79.19    78.1   78.13   78.91
   78.87    78.7   78.31   78.21   77.94   78.18    78.7   78.91   78.91    78.7
   78.22   78.17
                                                                                
                                                                                
                                                                                
                           77.78   77.77   77.76   77.75   77.73   77.73   77.72
   77.71   77.71    77.7   77.69   77.68   77.68   77.68   77.68   77.68   77.66
   77.66   77.65   77.65
                                                                                
                                                                                
                
    4008  4017.5  4044.8  4057.5  4074.8  4104.8  4157.5  4177.5  4220.4  4224.8
  4260.4  4404.8  4514.8  4524.8  4528.4  4558.4  4588.4  4596.3  4726.3    4730
  4758.4  4788.4    4800    4857    4869  4915.9  4930.7  4941.5 4974.29  4974.4
 4974.51  4974.6 4974.71  4974.8  4977.8  4980.3  4983.1  4987.8  4989.4  4991.3
  4994.1  4994.2  4996.6  4999.5  5005.6  5005.7  5007.4  5008.2  5009.8  5015.5
  5015.6  5022.6  5023.4 5023.49  5023.6 5023.71  5040.6  5062.5  5097.5  5138.7
  5145.7    5159  5168.8  5185.1  5193.7    5199  5203.7    5249  5253.7  5353.7
    5359    5419    5439  5453.7  5463.7    5469    5479  5483.7  5493.7    5499
    5509  5513.7
    77.3   77.76   78.31   78.91      79   79.15   79.41   80.01   79.61   79.52
   78.98   79.41   79.87   79.91   79.93   80.05   80.18   80.21   79.39    79.4
    79.5    80.1   80.07    79.9   79.82    79.5    79.4   79.08   78.78   81.98
   81.98   81.98   81.98   81.98   81.97   81.96   81.95   81.93   81.93   81.92
   81.91   81.91    81.9   81.89   81.88   81.88   81.88   81.88   81.88   81.86
   81.86   81.85   81.85   81.85   81.85   78.65   78.85   78.93   78.79   78.63
    78.6    78.9   79.29   79.67   79.25    79.3   79.19    78.1   78.13   78.91
   78.87    78.7   78.31   78.21   77.94   78.18    78.7   78.91   78.91    78.7
   78.22   78.17
                                                                                
                                                                                
                                                                                
                           77.78   77.77   77.76   77.75   77.73   77.73   77.72
   77.71   77.71    77.7   77.69   77.68   77.68   77.68   77.68   77.68   77.66
   77.66   77.65   77.65
                                                                                
                                                                                
                
Pier Skew, UpSta & Num, DnSta & Num=  ,4989.4, 2 ,4989.4, 2 , 0 , 0 , 0 ,,
       1       1
   69.93   78.73
       1       1
   70.88   79.68
Pier Skew, UpSta & Num, DnSta & Num=  ,5008.2, 2 ,5008.2, 2 , 0 , 0 , 0 ,,
       1       1
    69.3   78.68
       1       1
   70.25   79.63
BR Coef= 1 , 1 , 0 ,1.25, 0 ,,,.8,0,2,0,
WSPro=,,,, 1 ,,,, 0 ,,,, 0 ,,,,-1 ,-1 ,-1 , 0 , 0 , 0 , 0 , 0
BC Design=,, 0 ,, 0 ,,,,,,
BC HTab HWMax=79.71

Type RM Length L Ch R = 1 ,6304    ,110,105,100
BEGIN DESCRIPTION:
Downstream Section of Bridge/Culvert/Weir
OAK FOREST DRIVE - XS 2
END DESCRIPTION:
XS GIS Cut Line= 6
 3098826.550490913866075.3726324      3098272.94     13869320.33
      3098210.03      13869459.4      3098211.13     13869592.41
      3098205.55     13869714.71 3097977.449156213871387.7770382
#Sta/Elev= 30
    1426   76.22    1698   75.48    1768   77.64    1918   77.63    1988   75.57
    2108   78.27    2298   75.63    2368   78.15    2508   77.96    2598   75.59
    2728   78.37    2898   75.32    3018   78.43    3188   75.24    3268   77.73
    3418   77.84    3488   75.52    3578   77.96    3798   75.83    4088   76.07
    4869   79.21  4971.5   77.68  4977.8   77.54  4994.1   70.31  5007.4   70.71
  5022.6   77.55  5040.6   77.83  5185.1   79.67  5253.9   77.77  6813.9   79.12
#Mann= 6 ,-1 , 0
    1426     .99       0    4869     .08       0  4971.5    .045       0
  5022.6     .04       0  5040.6     .08       0  5185.1     .99       0
#XS Ineff= 2 , 0
       0    4971    78.8 5022.36       0   78.78
Permanent Ineff=
       F       F
#Block Obstruct= 2 , 0
       0    4868   79.25               0
Bank Sta=4971.5,5022.6
XS Rating Curve= 0
Exp/Cntr=.5,.3

Type RM Length L Ch R = 1 ,6199.   ,494,494,407
BEGIN DESCRIPTION:
Interpolated channel - LIDAR overbanks
OAK FOREST DRIVE - XS 1
END DESCRIPTION:
XS GIS Cut Line= 4
       3098822.5     13865483.57      3098113.18     13869440.06
      3098100.93     13869712.39 3097915.422550513871392.1934475
#Sta/Elev= 30
   827.9   73.47  1117.9   76.02  1967.9   75.76  2027.9   77.99  2277.9   75.89
  2527.9   78.29  2577.9   75.85  2617.9   77.83  2827.9   77.75  2867.9   75.71
  2927.9   77.83  3137.9   78.06  3187.9   75.77  3217.9   77.55  3427.9   78.82
  3477.9   76.77  3607.9   78.93  3777.9   76.11  3977.9   78.89  4077.9   76.33
  4127.9   78.37  4567.9    77.8  4847.5   80.02  4967.5   78.05 4982.83   75.24
 4995.22   70.03 5007.94   71.06  5027.5   78.51  5190.1   78.55  6810.1   79.36
#Mann= 5 ,-1 , 0
   827.9     .99       0  4847.5     .08       0  4967.5    .045       0
  5027.5     .08       0  5190.1     .99       0
#XS Ineff= 2 , 0
       0                5023.699       0    78.8
Permanent Ineff=
       F       F
#Block Obstruct= 2 , 0
       0    4853    79.2               0
Bank Sta=4967.5,5027.5
XS Rating Curve= 0
Exp/Cntr=.3,.1

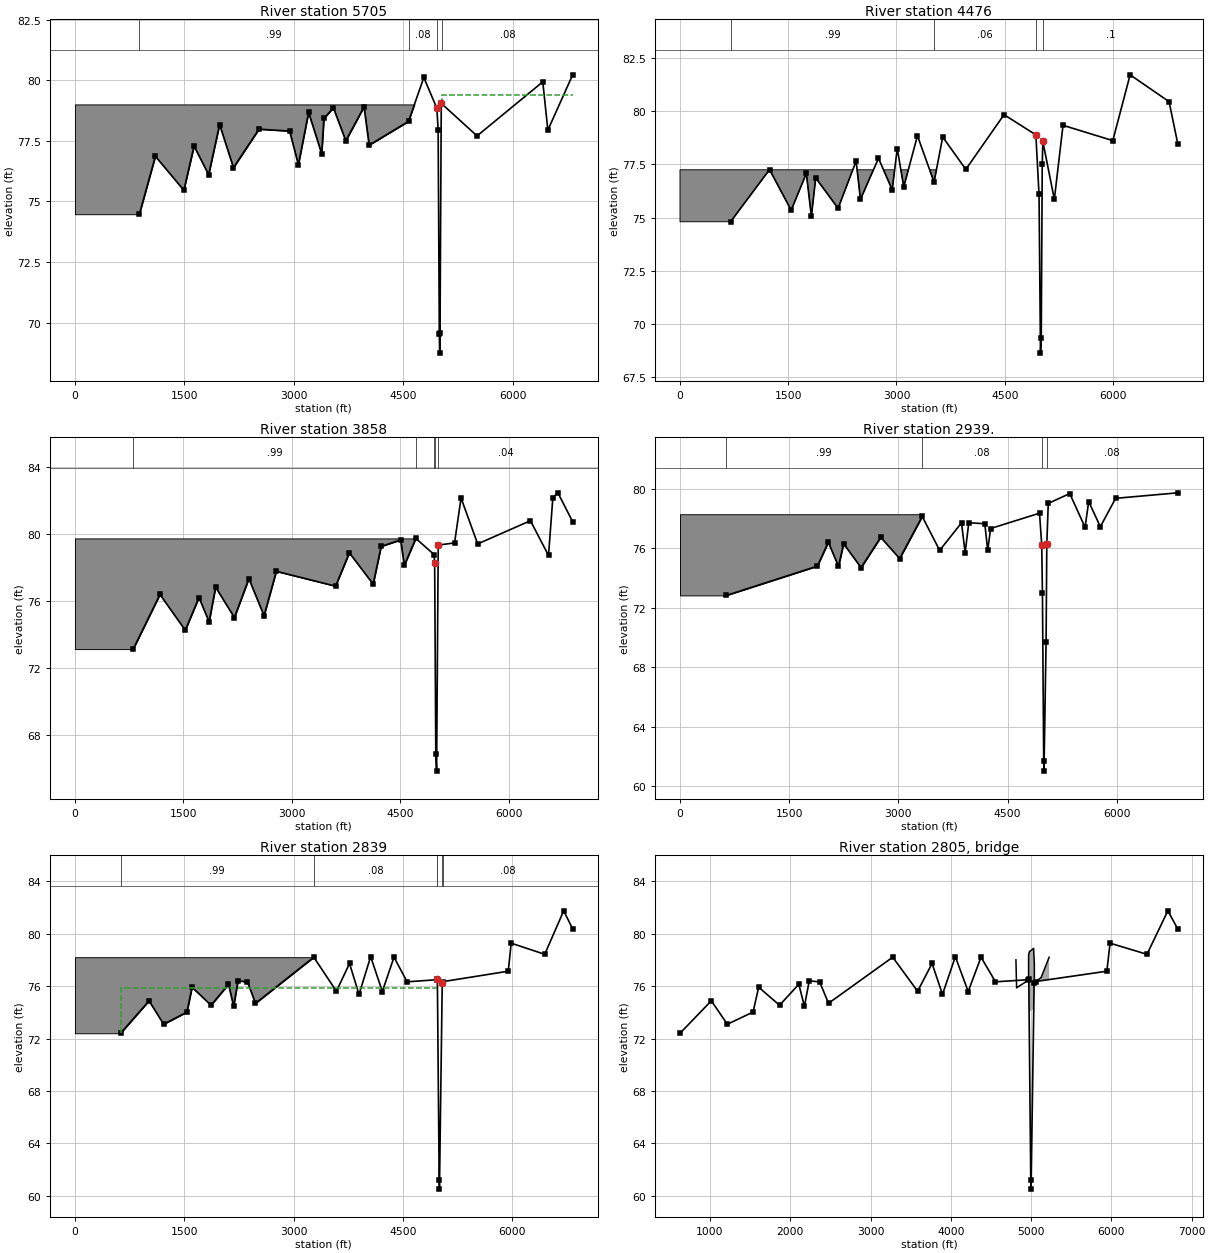
Type RM Length L Ch R = 1 ,5705    ,1229,1230,1231
BEGIN DESCRIPTION:
Cross Section X05
END DESCRIPTION:
XS GIS Cut Line= 5
      3098475.21     13865557.25      3097615.84     13869458.09
      3097611.11     13869753.19      3097710.46     13870406.64
  3097853.55223813871386.2248382
#Sta/Elev= 30
   882.8   74.47  1102.8   76.86  1492.8   75.46  1632.8   77.28  1832.8    76.1
  1982.8   78.17  2172.8   76.39  2522.8   77.98  2942.8    77.9  3062.8   76.51
  3202.8   78.67  3382.8   76.96  3412.8   78.42  3542.8   78.86  3712.8    77.5
  3962.8    78.9  4032.8   77.32  4572.8    78.3  4782.8   80.11  4961.6   78.84
  4979.2   77.93  4995.2   69.52  5000.5   68.74  5004.8   69.57    5022   79.04
  5037.7      79  5512.3    77.7  6413.3   79.93  6483.3   77.94  6823.3   80.22
#Mann= 4 ,-1 , 0
   882.8     .99       0  4572.8     .08       0  4961.6     .04       0
  5037.7     .08       0
#XS Ineff= 2 , 0
       0                    5030       0    79.4
Permanent Ineff=
       F       F
#Block Obstruct= 2 , 0
       0  4783.3      79               0
Bank Sta=4961.6,5022
XS Rating Curve= 0
Exp/Cntr=.3,.1

Type RM Length L Ch R = 1 ,4476    ,619,617,615
BEGIN DESCRIPTION:
Cross Section X04
END DESCRIPTION:
XS GIS Cut Line= 4
      3098047.07     13865596.89      3096385.53     13869278.46
      3096385.53     13869666.29      3096841.96     13871376.67
#Sta/Elev= 30
   700.9   74.81  1240.9   77.26  1540.9   75.35  1750.9   77.08  1820.9   75.06
  1880.9   76.87  2190.9   75.44  2440.9   77.66  2500.9   75.86  2750.9   77.79
  2940.9   76.31  3010.9   78.25  3100.9   76.45  3290.9   78.85  3520.9   76.67
  3640.9   78.79  3960.9   77.27  4490.9   79.84  4931.7   78.89  4975.7   76.09
  4995.8   68.64  5006.4   69.36  5020.3   77.53  5028.5   78.58  5187.9   75.86
  5307.9   79.34  5997.9   78.62  6237.9   81.71  6777.9   80.45  6898.1   78.48
#Mann= 4 ,-1 , 0
   700.9     .99       0  3520.9     .06       0  4931.7     .04       0
  5028.5      .1       0
#Block Obstruct= 2 , 0
       0    4700   77.25               0
Bank Sta=4931.7,5028.5
XS Rating Curve= 0
Exp/Cntr=.3,.1

Type RM Length L Ch R = 1 ,3858    ,918,919,920
BEGIN DESCRIPTION:
Cross Section X03
Begin E116-05-00 channel
END DESCRIPTION:
XS GIS Cut Line= 4
      3097087.74     13865541.39       3095773.7     13869338.64
      3095766.62     13869626.32      3096207.69     13871344.96
#Sta/Elev= 30
   806.1   73.12  1176.1   76.39  1526.1   74.25  1716.1   76.21  1856.1   74.75
  1946.1   76.83  2206.1   75.01  2406.1   77.34  2616.1   75.12  2786.1   77.78
  3606.1   76.89  3796.1   78.89  4126.1   77.01  4236.1   79.27  4506.1   79.66
  4556.1   78.13  4716.1   79.75  4969.6   78.78  4976.7   78.28  4992.8   66.84
  5003.8   65.81  5026.3   79.35  5252.1   79.48  5342.1   82.17  5572.1   79.42
  6302.1   80.81  6552.1   78.73  6612.1   82.19  6682.1   82.48  6886.4   80.75
#Mann= 5 ,-1 , 0
   806.1     .99       0  4716.1     .08       0  4969.6     .04       0
  4976.7    .045       0  5026.3     .04       0
#Block Obstruct= 2 , 0
       0  4716.1   79.75               0
Bank Sta=4976.7,5026.3
XS Rating Curve= 0
Exp/Cntr=.3,.1

Type RM Length L Ch R = 1 ,2939.   ,99,100,101
BEGIN DESCRIPTION:
Interpolated channel - LIDAR overbanks
BELLE GLADE STREET - XS 4
End E116-00-00 channel
END DESCRIPTION:
XS GIS Cut Line= 4
      3096298.57     13865370.46      3094853.79     13869358.61
       3094845.2     13869644.01      3094800.11     13871316.73
#Sta/Elev= 30
   637.1   72.84  1887.1   74.81  2037.1   76.42  2177.1   74.79  2247.1   76.32
  2487.1   74.71  2757.1   76.75  3017.1   75.32  3327.1   78.15  3567.1   75.87
  3867.1   77.72  3917.1   75.71  3967.1   77.73  4187.1   77.66  4227.1   75.87
  4267.1   77.34  4938.9   78.37  4968.9   76.24  4978.9   73.02 4996.21   61.68
 5000.19   61.02  5028.9   69.69  5038.9    76.3  5058.9   79.03  5354.4   79.69
  5564.4   77.42  5614.4   79.15  5774.4   77.46  5984.4   79.37  6837.7   79.74
#Mann= 4 ,-1 , 0
   637.1     .99       0  3327.1     .08       0  4968.9     .05       0
  5038.9     .08       0
#Block Obstruct= 2 , 0
       0    3327    78.3               0
Bank Sta=4968.9,5038.9
XS Rating Curve= 0
Exp/Cntr=.5,.3

Type RM Length L Ch R = 1 ,2839    ,61,61,61
BEGIN DESCRIPTION:
Upstream Section of Bridge/Culvert/Weir
BELLE GLADE STREET - XS 3
END DESCRIPTION:
XS GIS Cut Line= 4
      3096199.76     13865366.97      3094754.98     13869355.12
       3094746.4     13869640.52       3094701.3     13871313.25
#Sta/Elev= 30
   626.3    72.4  1016.3   74.88  1216.3   73.09  1536.3   74.02  1606.3   75.92
  1866.3   74.54  2106.3   76.14  2176.3   74.46  2236.3   76.41  2366.3   76.32
  2476.3   74.69  3276.3   78.21  3586.3   75.61  3766.3   77.73  3896.3   75.37
  4056.3   78.25  4216.3   75.59  4376.3   78.21  4556.3   76.33  4965.9   76.49
  4971.3   76.51  4995.8    61.2  4999.8    60.5    5038   76.27    5055   76.35
  5943.6   77.14  5983.6   79.28  6443.6   78.43  6703.6   81.75  6826.9   80.37
#Mann= 6 ,-1 , 0
   626.3     .99       0  3276.3     .08       0  4965.9     .04       0
  4971.3     .05       0    5038     .04       0    5055     .08       0
#XS Ineff= 2 , 0
       0 4970.93   75.87    5038       0    75.9
Permanent Ineff=
       F       F
#Block Obstruct= 2 , 0
       0  3276.3   78.21               0
Bank Sta=4971.3,5038
XS Rating Curve= 0
Exp/Cntr=.5,.3

Type RM Length L Ch R = 3 ,2805    ,,,
BEGIN DESCRIPTION:
BELLE GLADE STREET
Structure ID: E116-05-00-03
END DESCRIPTION:
Bridge Culvert--1,0,-1,-1, 0
Deck Dist Width WeirC Skew NumUp NumDn MinLoCord MaxHiCord MaxSubmerge Is_Ogee
10,37,3,0, 33, 33, , , .95, 0, ,,,
  4811.2  4819.2  4819.3  4872.6  4926.1  4965.9 4968.69  4968.8 4968.91  4971.3
  4977.6  4977.8 4977.93    4978  4978.1  4995.8  4999.8  5000.9  5004.1  5031.4
 5031.49 5031.58  5031.7    5032    5038 5040.59  5040.7 5040.81    5055  5070.6
  5124.2  5124.3  5224.9
   78.01   75.91   75.87   76.09   76.29   76.68   76.76   78.36   78.36   78.43
   78.62   78.63   78.63   78.63   78.63   78.71   78.73   78.74   78.75   78.88
   78.88   78.88   78.87   78.83   78.04    77.7    77.7   76.24   76.31    76.4
   76.65   76.65   78.21
                                                                                
                           74.03   74.03   74.11   74.13   74.14   74.15   74.28
   74.28
                        
  4811.2  4819.2  4819.3  4872.6  4926.1  4965.9 4968.69  4968.8 4968.91  4971.3
  4977.6  4977.8 4977.93    4978  4978.1  4995.8  4999.8  5000.9  5004.1  5031.4
 5031.49 5031.58  5031.7    5032    5038 5040.59  5040.7 5040.81    5055  5070.6
  5124.2  5124.3  5224.9
   78.01   75.91   75.87   76.09   76.29   76.68   76.76   78.36   78.36   78.43
   78.62   78.63   78.63   78.63   78.63   78.71   78.73   78.74   78.75   78.88
   78.88   78.88   78.87   78.83   78.04    77.7    77.7   76.24   76.31    76.4
   76.65   76.65   78.21
                                                                                
                           74.03   74.03   74.11   74.13   74.14   74.15   74.28
   74.28
                        
BR Coef= 1 , 1 , 0 ,1.25, 0 ,,,.8,0,2,0,
WSPro=,,,, 1 ,,,, 0 ,,,, 0 ,,,,-1 ,-1 ,-1 , 0 , 0 , 0 , 0 , 0
BC Design=,, 0 ,, 0 ,,,,,,
BC HTab HWMax=81.76