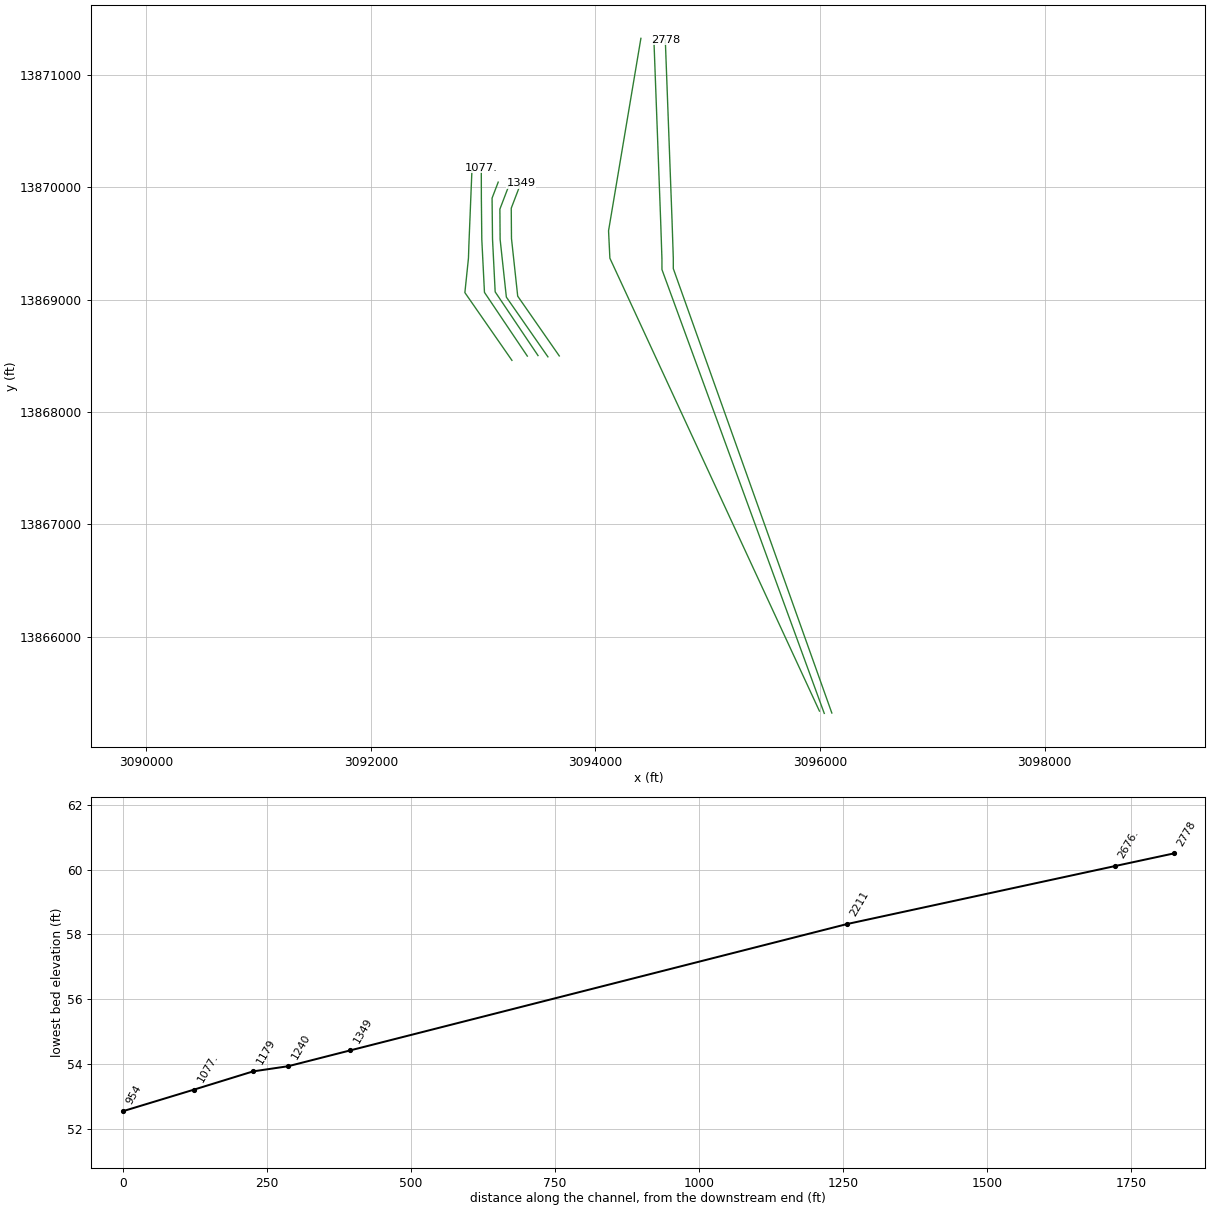
HEC-RAS study E116-05-00.prj: E116-05-00

--- E116-05-00.g01 (geometry) --- (continued)

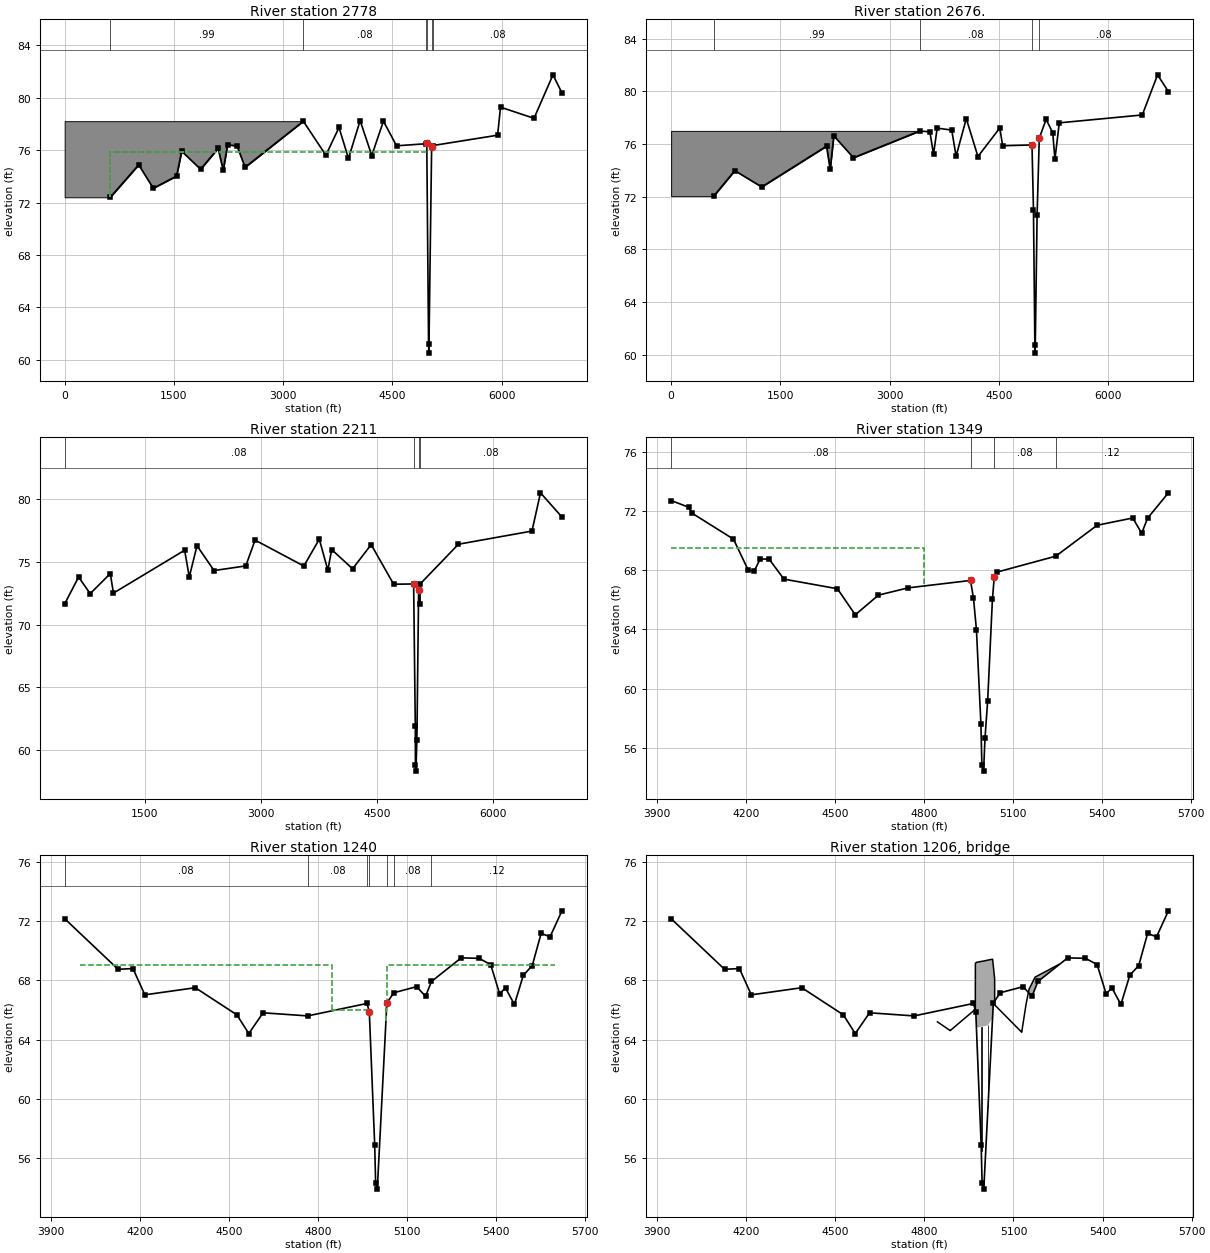
Type RM Length L Ch R = 1 ,2778    ,101,102,103
BEGIN DESCRIPTION:
Downstream Section of Bridge/Culvert/Weir
BELLE GLADE STREET - XS 2
END DESCRIPTION:
XS GIS Cut Line= 6
      3096104.62      13865319.4      3094693.37     13869275.66
      3094693.23     13869371.06      3094684.74     13869624.48
      3094682.02     13869705.58      3094622.02     13871313.25
#Sta/Elev= 30
   626.3    72.4  1016.3   74.88  1216.3   73.09  1536.3   74.02  1606.3   75.92
  1866.3   74.54  2106.3   76.14  2176.3   74.46  2236.3   76.41  2366.3   76.32
  2476.3   74.69  3276.3   78.21  3586.3   75.61  3766.3   77.73  3896.3   75.37
  4056.3   78.25  4216.3   75.59  4376.3   78.21  4556.3   76.33  4965.9   76.49
  4971.3   76.51  4995.8    61.2  4999.8    60.5    5038   76.27    5055   76.35
  5943.6   77.14  5983.6   79.28  6443.6   78.43  6703.6   81.75  6826.9   80.37
#Mann= 6 ,-1 , 0
   626.3     .99       0  3276.3     .08       0  4965.9     .04       0
  4971.3     .05       0    5038     .04       0    5055     .08       0
#XS Ineff= 2 , 0
       0 4970.93   75.87 5038.67       0   75.87
Permanent Ineff=
       F       F
#Block Obstruct= 2 , 0
       0  3276.3   78.21               0
Bank Sta=4971.3,5038
XS Rating Curve= 0
Exp/Cntr=.5,.3

Type RM Length L Ch R = 1 ,2676.   ,466,465,464
BEGIN DESCRIPTION:
Interpolated channel - LIDAR overbanks
BELLE GLADE STREET - XS 1
END DESCRIPTION:
XS GIS Cut Line= 6
      3096037.17     13865316.12      3094592.24     13869267.52
       3094592.1     13869362.92      3094583.61     13869616.34
      3094580.89     13869697.44      3094520.89     13871305.11
#Sta/Elev= 30
   584.2   72.04   874.2   73.98  1244.2   72.74  2134.2   75.84  2184.2   74.07
  2234.2   76.63  2504.2   74.96  3414.2   76.99  3554.2   76.93  3604.2   75.22
  3654.2   77.21  3854.2   77.06  3914.2   75.08  4054.2   77.93  4214.2   75.05
  4514.2   77.22  4554.2   75.87  4956.9   75.93  4976.9   70.99 4996.17   60.74
  5000.2   60.11  5026.9   70.63  5056.9   76.45  5150.5   77.87  5241.6   76.86
  5271.6   74.85  5331.6   77.61  6471.6   78.21  6681.6   81.26  6830.4   79.98
#Mann= 4 ,-1 , 0
   584.2     .99       0  3414.2     .08       0  4956.9     .05       0
  5056.9     .08       0
#Block Obstruct= 2 , 0
       0    3414      77               0
Bank Sta=4956.9,5056.9
XS Rating Curve= 0
Exp/Cntr=.3,.1

Type RM Length L Ch R = 1 ,2211    ,861,862,863
BEGIN DESCRIPTION:
Cross Section X02
END DESCRIPTION:
XS GIS Cut Line= 4
      3095994.36     13865336.45       3094128.6     13869368.72
      3094116.86     13869612.87      3094404.83     13871325.97
#Sta/Elev= 30
     464   71.66     644    73.8     794   72.48    1054   74.08    1094   72.52
    2014   75.94    2074   73.81    2174    76.3    2394   74.32    2804   74.69
    2924   76.75    3554   74.68    3754   76.82    3864   74.35    3914   75.99
    4184   74.46    4424   76.39    4714   73.23  4972.5   73.25  4994.1   61.88
  4995.7   58.83    5002   58.32  5014.7   60.81    5037   72.74  5053.8   71.66
    5057   73.25  5551.4   76.42  6501.4   77.47  6611.4   80.52  6888.6   78.59
#Mann= 4 ,-1 , 0
     464     .08       0  4972.5     .05       0    5037     .04       0
    5057     .08       0
Bank Sta=4972.5,5037
XS Rating Curve= 0
Exp/Cntr=.3,.1

Type RM Length L Ch R = 1 ,1349    ,108,108,108
BEGIN DESCRIPTION:
Interpolated channel - LIDAR overbanks
ECLIPSE DRIVE - XS 4
END DESCRIPTION:
XS GIS Cut Line= 5
      3093678.15     13868498.45      3093308.06     13869030.44
       3093252.6     13869544.46      3093250.56     13869813.78
      3093336.35     13870037.89
#Sta/Elev= 30
  3948.2    72.7  4008.2   72.24  4018.2   71.85  4158.2   70.09  4208.2   67.98
  4228.2   67.95  4248.2   68.75  4278.2   68.74  4328.2   67.39  4508.2   66.74
  4568.2   64.98  4646.3   66.31  4746.3    66.8  4956.3    67.3  4966.3   66.09
  4976.3   63.95 4991.33   57.57 4994.56   54.81 5000.22   54.42 5005.07   56.65
 5014.06   59.19 5030.11   66.06  5036.3   67.55  5046.3   67.87  5243.3   68.94
  5382.6   71.03  5502.6   71.52  5532.6   70.49  5552.6   71.51  5622.6   73.22
#Mann= 4 ,-1 , 0
  3948.2     .08       0  4956.3     .05       0  5036.3     .08       0
  5243.3     .12       0
#XS Ineff= 2 , 0
       0    4800    69.5               0
Permanent Ineff=
       F       F
Bank Sta=4956.3,5036.3
XS Rating Curve= 0
Exp/Cntr=.5,.3

Type RM Length L Ch R = 1 ,1240    ,61,61,61
BEGIN DESCRIPTION:
Upstream Section of Bridge/Culvert/Weir
ECLIPSE DRIVE - XS 3
END DESCRIPTION:
XS GIS Cut Line= 5
 3093577.012914213868490.3149143      3093206.93     13869022.31
      3093151.47     13869536.32      3093149.43     13869805.64
 3093235.212924213870029.7518798
#Sta/Elev= 30
  3947.3   72.15  4127.3   68.74  4177.3   68.79  4217.3   67.02  4387.3    67.5
  4527.3   65.67  4567.3   64.41  4615.4   65.81  4765.4    65.6  4965.4   66.44
  4973.1   65.87  4991.2   56.91  4994.4   54.31    5000   53.93  5032.2   66.47
  5055.4   67.16  5132.4   67.57  5162.4   66.92  5182.4   67.92  5282.4   69.51
  5342.4   69.48  5381.7   69.06  5411.7    67.1  5431.7   67.48  5461.7   66.37
  5491.7   68.34  5521.7   68.99  5551.7   71.16  5581.7   70.93  5621.7   72.68
#Mann= 7 ,-1 , 0
  3947.3     .08       0  4765.4     .08       0  4965.4     .04       0
  4973.1     .05       0  5032.2     .04       0  5055.4     .08       0
  5182.4     .12       0
#XS Ineff= 4 ,-1
    4000    4849      69    4849    4965      66    5029    5032    66.6
    5032    5600      69
Permanent Ineff=
       F       F       F       F
Bank Sta=4973.1,5032.2
XS Rating Curve= 0
Exp/Cntr=.5,.3

Type RM Length L Ch R = 3 ,1206    ,,,
BEGIN DESCRIPTION:
ECLIPSE DRIVE
Structure ID: E116-05-00-02
END DESCRIPTION:
Bridge Culvert--1,0,-1,-1, 0
Deck Dist Width WeirC Skew NumUp NumDn MinLoCord MaxHiCord MaxSubmerge Is_Ogee
10,38,3,0, 37, 37, , , .95, 0, ,,,
    4844  4887.1  4887.5  4968.2 4971.59  4971.7 4971.81  4973.1  4975.6 4975.71
  4975.8  4975.9  4991.2  4994.4    5000  5004.8  5013.7  5029.6 5029.69  5029.8
  5029.9  5032.2 5036.49  5036.6 5036.71  5046.8  5127.8  5128.2  5142.6  5143.2
  5152.6  5163.2  5172.6  5190.9  5213.2  5233.2  5253.2
    65.2   64.61   64.62   65.99   66.05   69.15   69.15   69.17   69.21   69.21
   69.21   69.21   69.27   69.28    69.3   69.32   69.36   69.42   69.42   69.42
    69.4   68.95   68.12   68.12   66.34   66.14    64.5   64.56   66.41   66.47
   67.41   67.83   68.21   68.41   68.64   68.86   69.07
                                                                                
           64.81   64.87   64.88    64.9   64.92   64.96   65.02
                                                                                
                                                        
    4844  4887.1  4887.5  4968.2 4971.59  4971.7 4971.81  4973.1  4975.6 4975.71
  4975.8  4975.9  4991.2  4994.4    5000  5004.8  5013.7  5029.6 5029.69  5029.8
  5029.9  5032.2 5036.49  5036.6 5036.71  5046.8  5127.8  5128.2  5142.6  5143.2
  5152.6  5163.2  5172.6  5190.9  5213.2  5233.2  5253.2
    65.2   64.61   64.62   65.99   66.05   69.15   69.15   69.17   69.21   69.21
   69.21   69.21   69.27   69.28    69.3   69.32   69.36   69.42   69.42   69.42
    69.4   68.95   68.12   68.12   66.34   66.14    64.5   64.56   66.41   66.47
   67.41   67.83   68.21   68.41   68.64   68.86   69.07
                                                                                
           64.81   64.87   64.88    64.9   64.92   64.96   65.02
                                                                                
                                                        
Pier Skew, UpSta & Num, DnSta & Num=  ,4991.7, 2 ,4991.7, 2 , 0 , 0 , 0 ,,
       2       2
   54.64   65.87
       2       2
   54.58   65.81
Pier Skew, UpSta & Num, DnSta & Num=  ,5014.2, 2 ,5014.2, 2 , 0 , 0 , 0 ,,
       2       2
   57.63      66
       2       2
   57.57   65.94
BR Coef= 1 , 1 , 0 ,1.25, 0 ,,,.8,0,2,0,
WSPro=,,,, 1 ,,,, 0 ,,,, 0 ,,,,-1 ,-1 ,-1 , 0 , 0 , 0 , 0 , 0
BC Design=,, 0 ,, 0 ,,,,,,
BC HTab HWMax=72.68

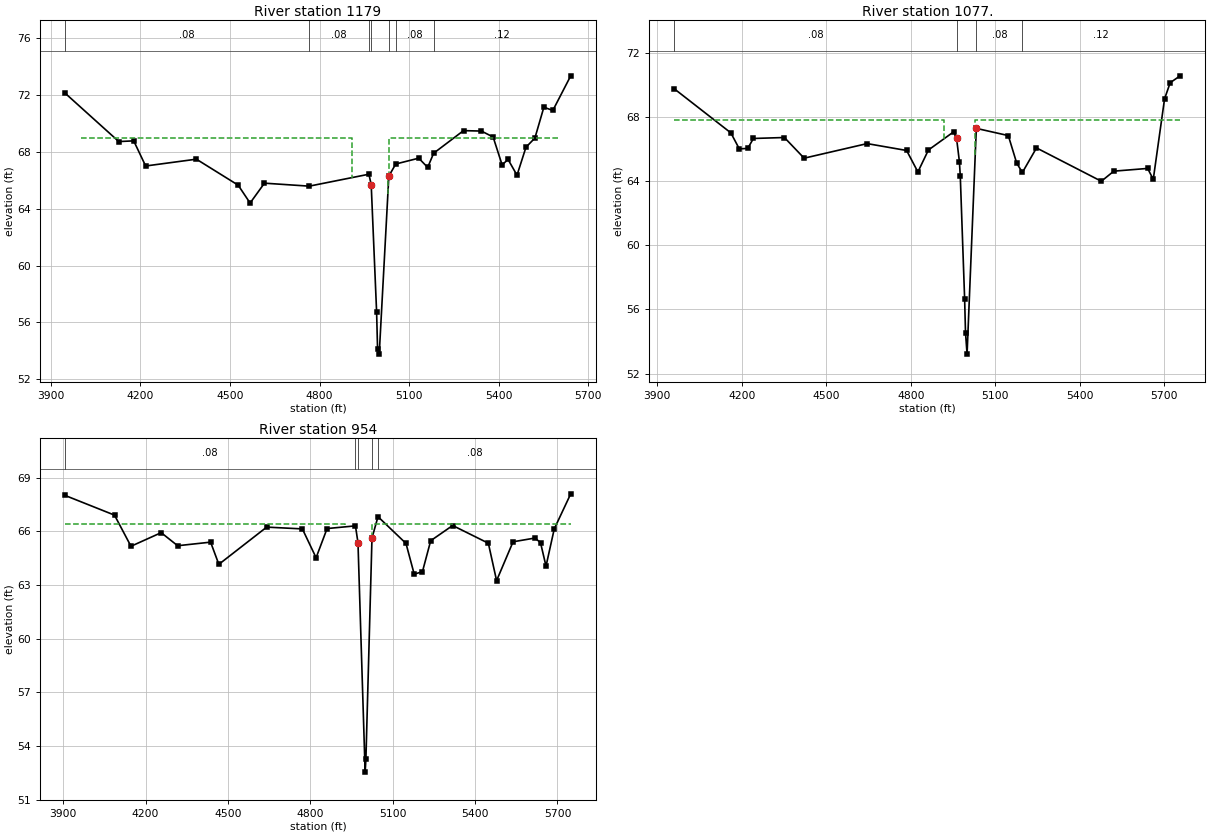
Type RM Length L Ch R = 1 ,1179    ,103,102,101
BEGIN DESCRIPTION:
Downstream Section of Bridge/Culvert/Weir
ECLIPSE DRIVE - XS 2
END DESCRIPTION:
XS GIS Cut Line= 6
 3093488.948833413868501.5847383      3093107.42     13869068.83
      3093096.49     13869285.89      3093083.75     13869539.03
      3093079.84     13869903.27 3093134.4664631 13870045.801784
#Sta/Elev= 30
  3947.3   72.15  4127.3   68.74  4177.3   68.79  4217.3   67.02  4387.3    67.5
  4527.3   65.67  4567.3   64.41  4615.4   65.81  4765.4    65.6  4965.4   66.44
  4973.1   65.71  4991.2   56.75  4994.4   54.15    5000   53.77  5032.2   66.31
  5055.4   67.16  5132.4   67.57  5162.4   66.92  5182.4   67.92  5282.4   69.51
  5342.4   69.48  5381.7   69.06  5411.7    67.1  5431.7   67.48  5461.7   66.37
  5491.7   68.34  5521.7   68.99  5551.7   71.16  5581.7   70.93  5641.7   73.37
#Mann= 7 ,-1 , 0
  3947.3     .08       0  4765.4     .08       0  4965.4     .04       0
  4973.1     .05       0  5032.2     .04       0  5055.4     .08       0
  5182.4     .12       0
#XS Ineff= 4 ,-1
    4000    4910      69    4910    4965    65.2    5029    5032      66
    5032    5600      69
Permanent Ineff=
       F       F       F       F
Bank Sta=4973.1,5032.2
XS Rating Curve= 0
Exp/Cntr=.5,.3

Type RM Length L Ch R = 1 ,1077.   ,129,124,124
BEGIN DESCRIPTION:
Interpolated channel - LIDAR overbanks
ECLIPSE DRIVE - XS 1
END DESCRIPTION:
XS GIS Cut Line= 6
      3093393.63     13868496.93       3093012.1     13869064.18
      3093001.17     13869281.24      3092988.43     13869534.38
      3092984.52     13869898.62      3092983.86     13870173.95
#Sta/Elev= 30
  3961.7   69.76  4161.7   67.02  4191.7   66.02  4221.7   66.05  4241.7   66.67
  4351.7   66.73  4421.7   65.44  4645.3   66.35  4785.3   65.92  4825.3   64.58
  4862.6   65.95  4952.6   67.09  4962.6   66.67  4972.6   65.22  4975.7   64.32
 4991.09   56.67 4994.25   54.54 4999.77   53.21  5032.6    67.3  5146.1   66.85
  5176.1   65.12  5196.1   64.55  5246.1   66.08  5476.1      64  5520.4   64.63
  5640.4    64.8  5660.4   64.12  5700.4   69.14  5720.4   70.15  5755.7   70.58
#Mann= 4 ,-1 , 0
  3961.7     .08       0  4962.6     .05       0  5032.6     .08       0
  5196.1     .12       0
#XS Ineff= 2 , 0
       0 4916.77    67.8 5028.68       0    67.8
Permanent Ineff=
       F       F
Bank Sta=4962.6,5032.6
XS Rating Curve= 0
Exp/Cntr=.3,.1

Type RM Length L Ch R = 1 ,954     ,134,133,131
BEGIN DESCRIPTION:
Cross Section X01
END DESCRIPTION:
XS GIS Cut Line= 5
  3093256.57834713868459.0584889      3092837.76     13869062.04
      3092869.59     13869369.21      3092873.05     13869477.67
 3092901.153655113870167.1317832
#Sta/Elev= 30
  3906.7      68  4086.7    66.9  4146.7   65.16  4256.7   65.92  4316.7   65.19
  4436.7   65.39  4466.7   64.15  4640.9   66.23  4770.9   66.13  4820.9   64.52
  4860.9   66.15  4964.2    66.3  4973.4   65.36  4999.5   52.54  5002.3   53.28
  5024.4   65.62  5046.366.81246  5148.2   65.32  5178.2    63.6  5208.2   63.74
  5238.2   65.47  5318.2   66.32  5448.2   65.33  5478.2   63.24  5538.2   65.41
  5618.2   65.62  5638.2   65.36  5658.2   64.05  5688.2   66.13  5748.2   68.09
#Mann= 5 ,-1 , 0
  3906.7     .08       0  4964.2     .04       0  4973.4     .05       0
  5024.4     .04       0  5046.3     .08       0
#XS Ineff= 2 , 0
       0    4925    66.4  5024.4       0    66.4
Permanent Ineff=
       F       F
Bank Sta=4973.4,5024.4
XS Rating Curve= 0
Exp/Cntr=.3,.1