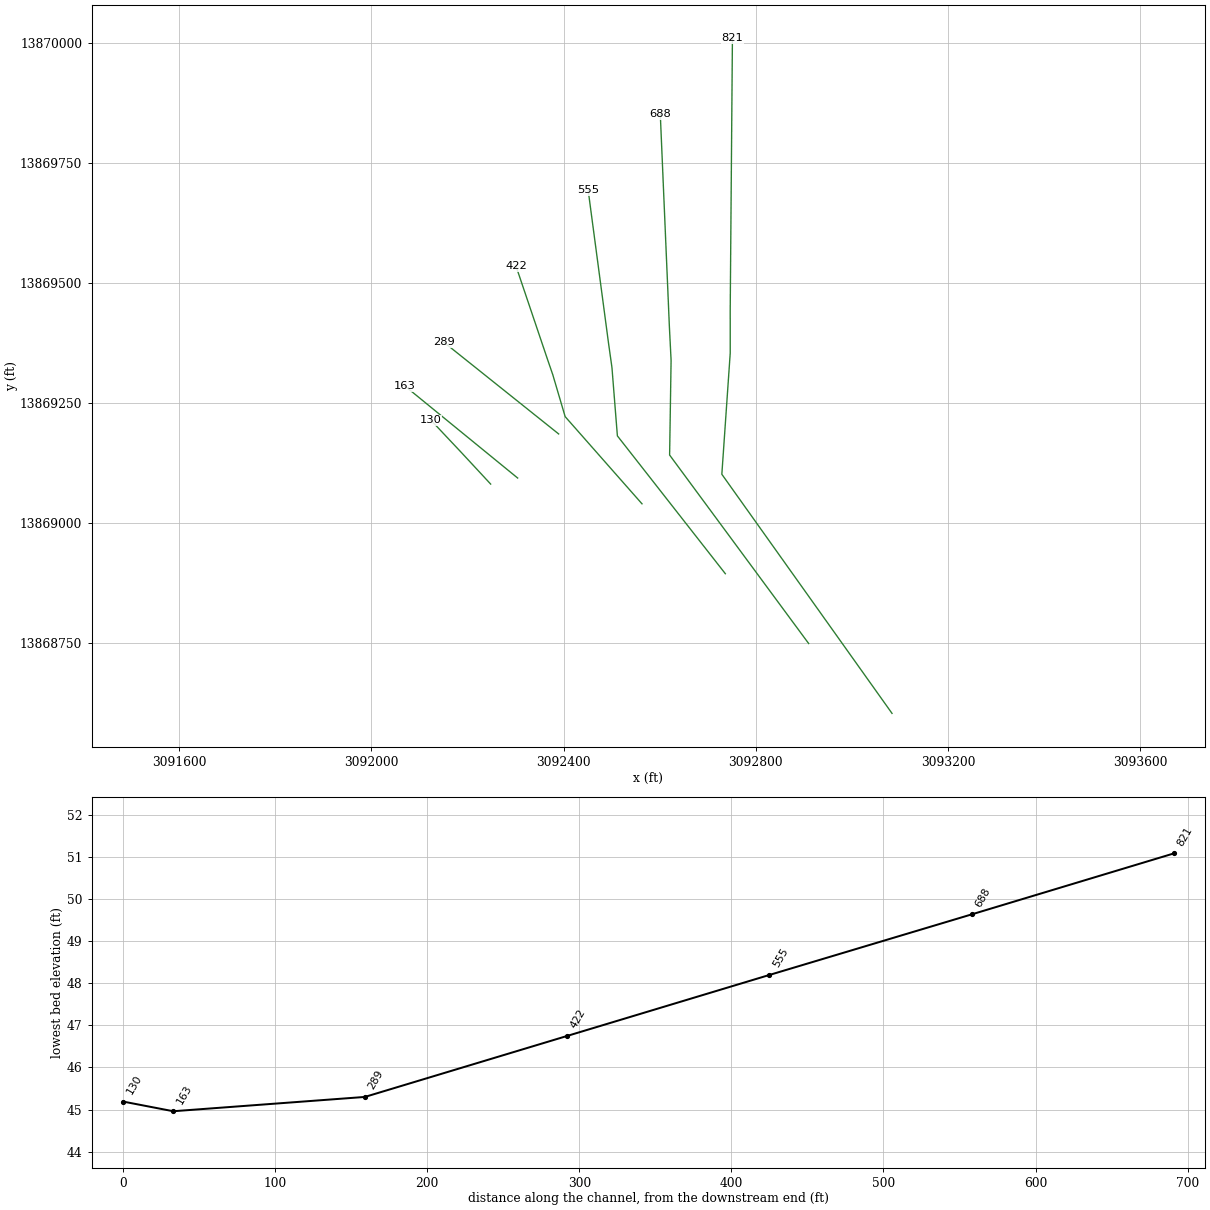
HEC-RAS study E116-05-00.prj: E116-05-00

--- E116-05-00.g01 (geometry) --- (continued)

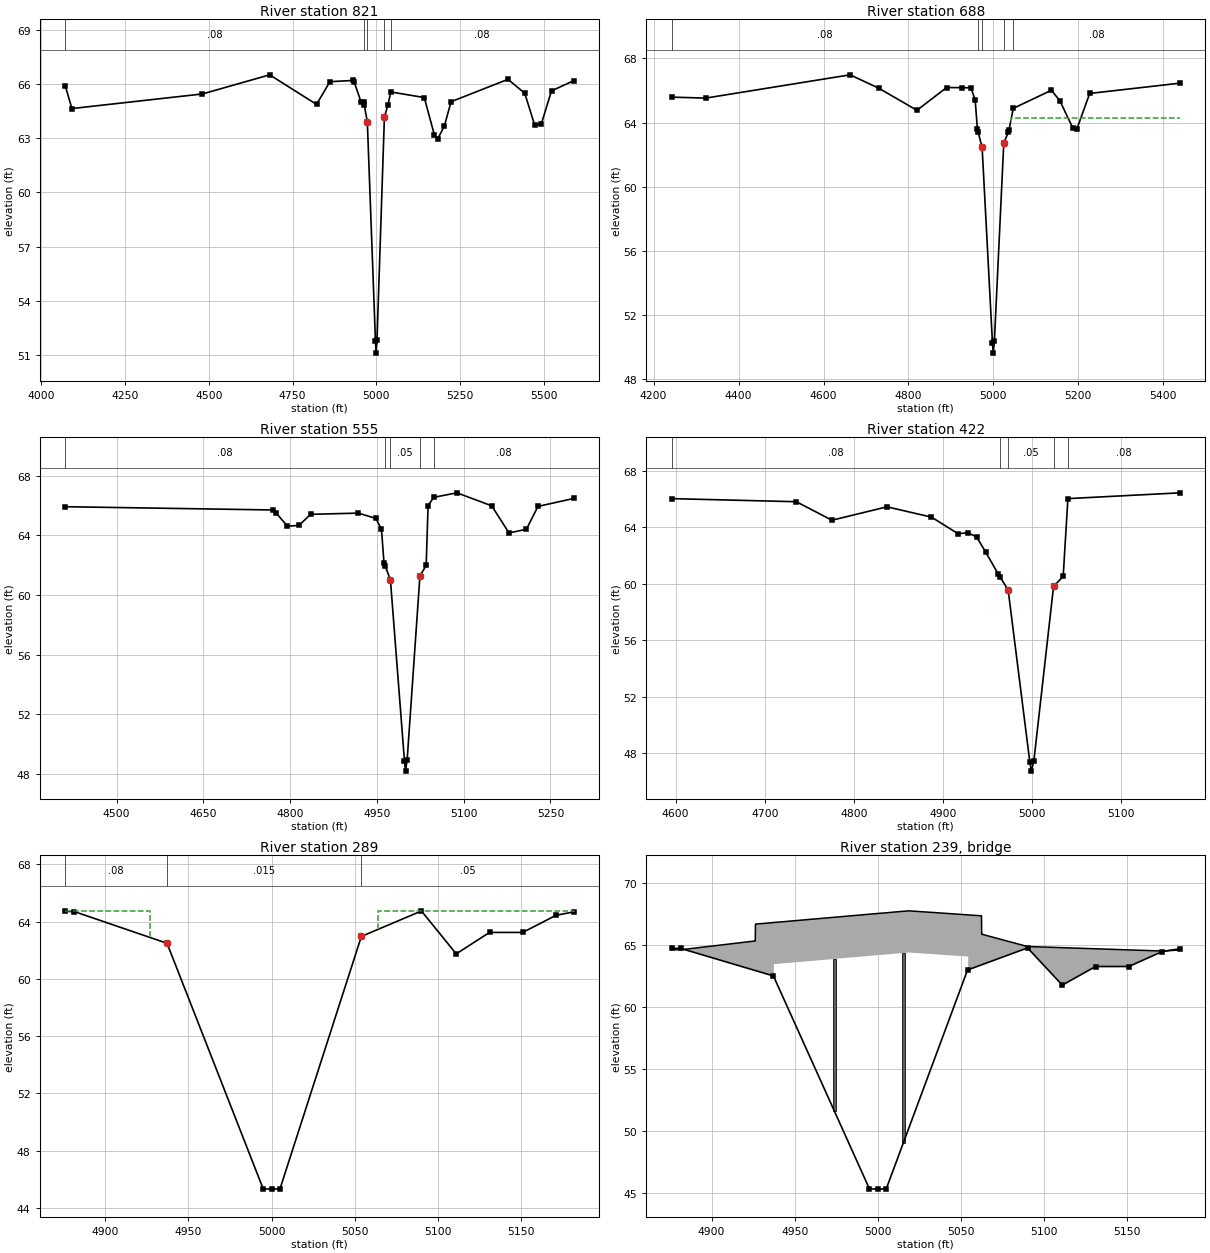
Type RM Length L Ch R = 1 ,821     ,135,133,130
BEGIN DESCRIPTION:
Cross Section X0.9 INTERPOLATED
END DESCRIPTION:
XS GIS Cut Line= 5
      3093083.17      13868604.4      3092729.09      13869101.9
      3092746.54      13869354.1       3092746.5      13869443.1
       3092751.1      13870008.9
#Sta/Elev= 29
    4071   65.92    4091   64.65    4481   65.46  4681.7   66.52  4821.7   64.88
  4861.7   66.14  4931.7   66.21  4934.4   66.11  4954.4   65.03  4962.3   65.04
  4964.2   64.85  4973.4   63.91  4997.7   51.75  4999.5   51.09  5002.3   51.83
  5024.4   64.17  5035.2   64.87  5043.5   65.57  5143.5   65.26  5173.5    63.2
  5183.5   62.96  5203.5   63.68  5223.5   65.03  5393.5   66.27  5443.5    65.5
  5473.5   63.72  5493.5   63.82  5523.5   65.63  5589.3   66.19
#Mann= 5 ,-1 , 0
    4071     .08       0  4964.2     .04       0  4973.4     .05       0
  5024.4     .04       0  5043.5     .08       0
#XS Ineff= 2 , 0
       0                 5032.32       0    64.5
Permanent Ineff=
       F       F
Bank Sta=4973.4,5024.4
XS Rating Curve= 0
Exp/Cntr=.3,.1

Type RM Length L Ch R = 1 ,688     ,134,133,131
BEGIN DESCRIPTION:
Cross Section X0.8 INTERPOLATED
END DESCRIPTION:
XS GIS Cut Line= 5
      3092909.77      13868749.7      3092620.42      13869141.9
       3092623.5       13869339.      3092619.96      13869408.6
      3092601.04      13869850.8
#Sta/Elev= 25
  4242.5   65.59  4322.5   65.53  4662.5   66.98  4729.9   66.15  4819.9   64.77
  4889.9   66.19    4927   66.18    4947   66.17    4957   65.43  4962.3   63.59
  4964.2    63.4  4973.4   62.46  4997.7    50.3  4999.5   49.64  5002.3   50.38
  5024.4   62.72  5035.2   63.42  5036.7   63.54  5046.7   64.89  5136.7   66.02
  5156.7   65.35  5186.7   63.68  5196.7   63.62  5226.7   65.82  5439.3   66.46
#Mann= 5 ,-1 , 0
  4242.5     .08       0  4964.2     .04       0  4973.4     .05       0
  5024.4     .04       0  5046.7     .08       0
#XS Ineff= 2 , 0
                         5040.24          64.292
Permanent Ineff=
       F       F
Bank Sta=4973.4,5024.4
XS Rating Curve= 0
Exp/Cntr=.3,.1

Type RM Length L Ch R = 1 ,555     ,135,133,130
BEGIN DESCRIPTION:
Cross Section X0.7 INTERPOLATED
END DESCRIPTION:
XS GIS Cut Line= 5
      3092736.37       13868895.      3092511.75      13869181.8
      3092500.46      13869323.9      3092493.41       13869374.
      3092450.99      13869692.7
#Sta/Elev= 25
  4411.1   65.92  4771.1    65.7  4775.4   65.52  4795.4   64.61  4815.4   64.67
  4835.4   65.41  4917.9   65.49  4947.9   65.14  4957.9   64.43  4962.3   62.15
  4964.2   61.96  4973.4   61.02  4997.7   48.86  4999.5    48.2  5002.3   48.94
  5024.4   61.28  5035.2   61.98  5038.5      66  5048.5   66.55  5088.5   66.85
  5148.5   65.98  5178.5   64.16  5208.5   64.41  5228.5   65.94    5290   66.47
#Mann= 5 ,-1 , 0
  4411.1     .08       0  4964.2     .04       0  4973.4     .05       0
  5024.4     .04       0  5048.5     .08       0
#XS Ineff= 2 , 0
                         5048.16          64.438
Permanent Ineff=
       F       F
Bank Sta=4973.4,5024.4
XS Rating Curve= 0
Exp/Cntr=.3,.1

Type RM Length L Ch R = 1 ,422     ,134,133,131
BEGIN DESCRIPTION:
Cross Section X0.6 INTERPOLATED
TC JESTER - XS 4
END DESCRIPTION:
XS GIS Cut Line= 5
      3092562.97      13869040.4      3092403.08      13869221.8
      3092377.42      13869308.8      3092366.87      13869339.5
      3092300.94      13869534.6
#Sta/Elev= 19
  4595.5   66.04  4735.5   65.82  4775.5   64.51  4837.3   65.46  4887.3   64.73
  4917.3   63.55    4928   63.63    4938   63.33    4948   62.27  4962.3    60.7
  4964.2   60.51  4973.4   59.57  4997.7   47.41  4999.5   46.75  5002.3   47.49
  5024.4   59.83  5035.2   60.53  5040.5   66.04  5166.4   66.45
#Mann= 5 ,-1 , 0
  4595.5     .08       0  4964.2     .04       0  4973.4     .05       0
  5024.4     .04       0  5040.5     .08       0
#XS Ineff= 2 , 0
                         5056.08          64.584
Permanent Ineff=
       F       F
Bank Sta=4973.4,5024.4
XS Rating Curve= 0
Exp/Cntr=.5,.3

Type RM Length L Ch R = 1 ,289     ,126,126,126
BEGIN DESCRIPTION:
Upstream Section of Bridge/Culvert/Weir
TC JESTER - XS 3
END DESCRIPTION:
XS GIS Cut Line= 2
      3092389.57     13869185.78      3092150.89     13869376.47
#Sta/Elev= 13
    4876   64.72  4881.4   64.71 4937.21   62.49 4994.98   45.32 5000.04    45.3
 5005.09   45.32 5053.99   62.97  5090.1   64.75    5111   61.75    5131   63.25
    5151   63.25    5171   64.45  5181.5   64.68
#Mann= 3 ,-1 , 0
    4876     .08       0 4937.21    .015       0 5053.99     .05       0
#XS Ineff= 2 , 0
       0    4927   64.76    5064       0   64.73
Permanent Ineff=
       F       F
Bank Sta=4937.21,5053.99
XS Rating Curve= 0
Exp/Cntr=.5,.3

Type RM Length L Ch R = 3 ,239     ,,,
BEGIN DESCRIPTION:
TC JESTER
Structure ID: E116-05-00-01
END DESCRIPTION:
Bridge Culvert--1,0,-1,-1, 0
Deck Dist Width WeirC Skew NumUp NumDn MinLoCord MaxHiCord MaxSubmerge Is_Ogee
10,100,2.6,0, 33, 33, , , .95, 0, ,,,
    4876  4881.4  4926.2 4926.29  4926.4 4926.51  4932.7 4937.41  4937.5  4941.1
  4943.8  4995.1  5000.3  5004.9  5005.1  5008.8    5018  5018.6  5031.8  5035.3
 5054.39  5054.5  5058.9 5062.29  5062.4 5062.51  5062.7  5090.1    5111    5131
    5151    5171  5181.8
   64.61    64.6   65.31   65.31   66.67   66.67   66.74    66.8    66.8   66.84
   66.87   67.47   67.53   67.58   67.58   67.63   67.73   67.74   67.62   67.59
   67.41   67.41   67.37   67.34   67.34   65.84   65.85   64.86   64.77   64.68
   64.59    64.5   64.58
                                                                   63.44   63.48
   63.51   64.11   64.17   64.22   64.22   64.27   64.37   64.38   64.26   64.23
   64.05
                        
    4876  4881.4  4926.2 4926.29  4926.4 4926.51  4932.7 4937.41  4937.5  4941.1
  4943.8  4995.1  5000.3  5004.9  5005.1  5008.8    5018  5018.6  5031.8  5035.3
 5054.39  5054.5  5058.9 5062.29  5062.4 5062.51  5062.7  5090.1    5111    5131
    5151    5171  5181.8
   64.61    64.6   65.31   65.31   66.67   66.67   66.74    66.8    66.8   66.84
   66.87   67.47   67.53   67.58   67.58   67.63   67.73   67.74   67.62   67.59
   67.41   67.41   67.37   67.34   67.34   65.84   65.85   64.86   64.77   64.68
   64.59    64.5   64.58
                                                                   63.44   63.48
   63.51   64.11   64.17   64.22   64.22   64.27   64.37   64.38   64.26   64.23
   64.05
                        
Pier Skew, UpSta & Num, DnSta & Num=  ,4973.9, 2 ,4973.9, 2 , 0 , 0 , 0 ,,
     1.6     1.6
   49.06   64.87
     1.6     1.6
   48.78   64.59
Pier Skew, UpSta & Num, DnSta & Num=  ,5015.3, 2 ,5015.3, 2 , 0 , 0 , 0 ,,
     1.6     1.6
   45.97   65.35
     1.6     1.6
   45.69   65.07
BR Coef= 1 , 1 , 0 ,1.25, 0 ,,,.8,0,2,0,
WSPro=,,,, 1 ,,,, 0 ,,,, 0 ,,,,-1 ,-1 ,-1 , 0 , 0 , 0 , 0 , 0
BC Design=,, 0 ,, 0 ,,,,,,
BC HTab HWMax=64.75

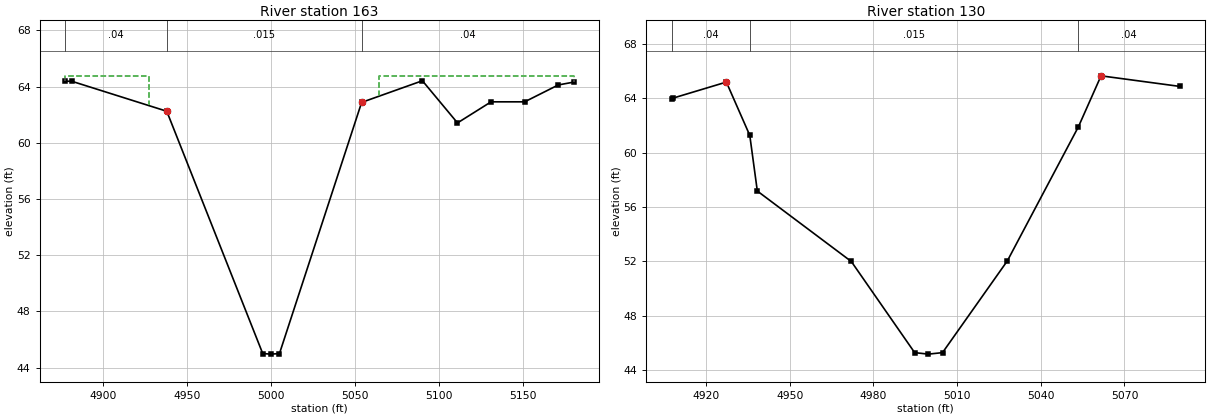
Type RM Length L Ch R = 1 ,163     ,35,33,30
BEGIN DESCRIPTION:
Downstream Section of Bridge/Culvert/Weir
TC JESTER - XS 2
END DESCRIPTION:
XS GIS Cut Line= 2
      3092304.26     13869094.07      3092069.73     13869285.47
#Sta/Elev= 13
  4877.4   64.38  4881.4   64.37 4937.88   62.24 4995.02      45 4999.99   44.96
 5004.99      45 5053.92   62.87  5090.1   64.41    5111   61.41    5131   62.91
    5151   62.91    5171   64.11  5180.1   64.31
#Mann= 3 ,-1 , 0
  4877.4     .04       0 4937.88    .015       0 5053.92     .04       0
#XS Ineff= 2 , 0
       0    4927   64.76    5064       0   64.73
Permanent Ineff=
       F       F
Bank Sta=4937.88,5053.92
XS Rating Curve= 0
Exp/Cntr=.5,.3

Type RM Length L Ch R = 1 ,130     ,0,0,0
BEGIN DESCRIPTION:
Cross Section X0.5 INTERPOLATED
TC JESTER - XS 1
Begin E116-00-00 channel
END DESCRIPTION:
XS GIS Cut Line= 3
      3092248.07      13869081.5      3092186.32     13869148.08
      3092123.65     13869214.56
#Sta/Elev= 13
  4907.7   63.98    4908      64  4927.3   65.19  4935.7   61.27  4938.4   57.18
 4972.09      52 4994.79    45.3  4999.7   45.19 5004.78    45.3 5028.03   52.05
  5053.5   61.91  5061.6   65.65  5089.9   64.87
#Mann= 3 ,-1 , 0
  4907.7     .04       0  4935.7    .015       0  5053.5     .04       0
Bank Sta=4927.3,5061.6
XS Rating Curve= 0
Exp/Cntr=.3,.1

Chan Stop Cuts=-1